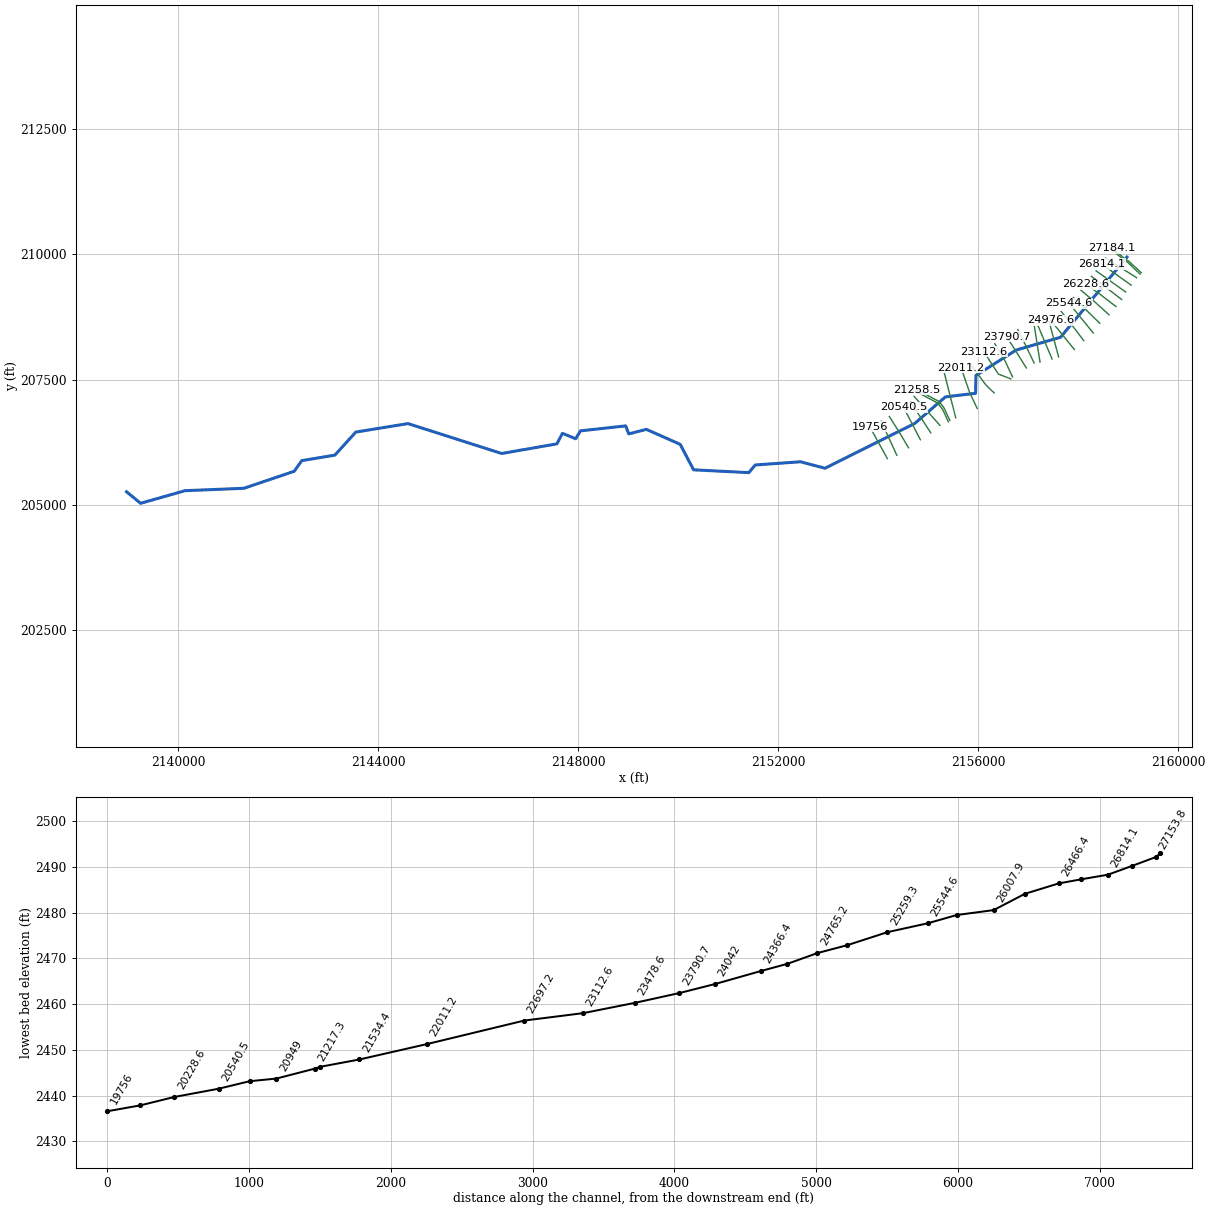
--- KITCHENCK.prj (project) ---

Proj Title=KITCHENCK
Current Plan=p01
Default Exp/Contr=0,0
English Units
Geom File=g01
Flow File=f01
Plan File=p01
BEGIN DESCRIPTION:
END DESCRIPTION:
DSS Export Rating Curves= 0
DSS Export Rating Curve Sorted= 0
DSS Export Volume Flow Curves= 0
DXF OffsetX= 0
DXF OffsetY= 0
DXF ScaleX= 0
DXF ScaleY= 0

--- KITCHENCK.p01 (plan) ---

Plan Title=Floodplain
Program Version=4.00
Geom File=g01
Flow File=f01
K Sum by GR=0
Std Step Tol=0.01
Critical Tol=0.01
Num of Std Step Trials=20
Max Error Tol=0.3
Flow Tol Ratio=0.001
Split Flow NTrial=30
Split Flow Tol=0.02
Split Flow Ratio=0.02
Log Output Level=0
Friction Slope Method=1
Unsteady Friction Slope Method=2
Unsteady Bridges Friction Slope Method=1
Global Log Level=0
CheckData=False
Run HTab=0
Run UNet=0
Run PostProcess=0
UNET Theta=0
UNET Theta Warmup=0
UNET ZTol=0
UNET ZSATol=0
UNET MxIter=0
UNET MaxInSteps=0
UNET DtIC=0
UNET DtMin=0
UNET MaxCRTS=0
UNET WFStab=0
UNET SFStab=0
UNET WFX=0
UNET SFX=0
UNET DSS MLevel=0
UNET DZMax Abort=0
UNET Convert EG Bridges=0
UNET Use Existing IB Tables=0
UNET Froude Limit=0
UNET Froude Power=0
Write IC File=0
Echo Input=False
Echo Output=False
Write Detailed=0

--- KITCHENCK.f01 (steady flow) ---

Flow Title=NFF Regression Equation
Program Version=4.10
Number of Profiles= 1
Profile Names=P100yr
River Rch & RM=KITCHENCK,Main            ,27184.1
 549.232
River Rch & RM=KITCHENCK,Main            ,26228.6
573.2224
River Rch & RM=KITCHENCK,Main            ,25748.2
668.0145
River Rch & RM=KITCHENCK,Main            ,23790.7
725.4513
River Rch & RM=KITCHENCK,Main            ,21534.4
796.8574
River Rch & RM=KITCHENCK,Main            ,21258.5
 922.524
River Rch & RM=KITCHENCK,Main            ,20949
947.8641
River Rch & RM=KITCHENCK,Main            ,19756
1032.262
River Rch & RM=KITCHENCK,Main            ,19154.1
1072.083
River Rch & RM=KITCHENCK,Main            ,16687.4
1167.259
River Rch & RM=KITCHENCK,Main            ,15422.5
1215.498
River Rch & RM=KITCHENCK,Main            ,13977.8
1347.963
River Rch & RM=KITCHENCK,Main            ,9776
1441.238
River Rch & RM=KITCHENCK,Main            ,536.2
1590.995
River Rch & RM=KITCHENCK,Main            ,173.8
1592.003
Boundary for River Rch & Prof#=KITCHENCK,Main            , 1
Up Type= 0
Dn Type= 3
Dn Slope=0.0085
DSS Import GetInterval= 0
DSS Import GetPeak= 0
DSS Import FillOption= 0

--- KITCHENCK.g01 (geometry) ---

Geom Title=USGS 1m DEM
Program Version=4.10

River Reach=KITCHENCK       ,Main
Reach XY= 30
     2158976.748      209945.914     2157648.623      208344.351
      2156761.47      208089.143     2155957.651      207582.198
     2155949.838      207225.427      2155346.54      207153.379
     2154734.561      206623.865     2152938.554      205728.032
     2152446.366      205857.372     2151541.852      205793.136
     2151415.984      205640.358     2150310.516      205696.348
     2150042.286      206205.896     2149366.939      206504.507
     2149013.641       206414.23     2148953.745      206573.952
     2148050.099      206474.993     2147952.877      206317.007
     2147687.251      206425.514     2147578.744      206215.445
     2146472.842      206022.737     2144599.578      206619.959
     2143556.175      206450.688     2143137.772       205989.75
     2142475.446      205879.507     2142324.404      205667.702
      2141317.46      205327.424     2140139.508      205279.681
      2139252.79      205027.511     2138971.276      205259.266

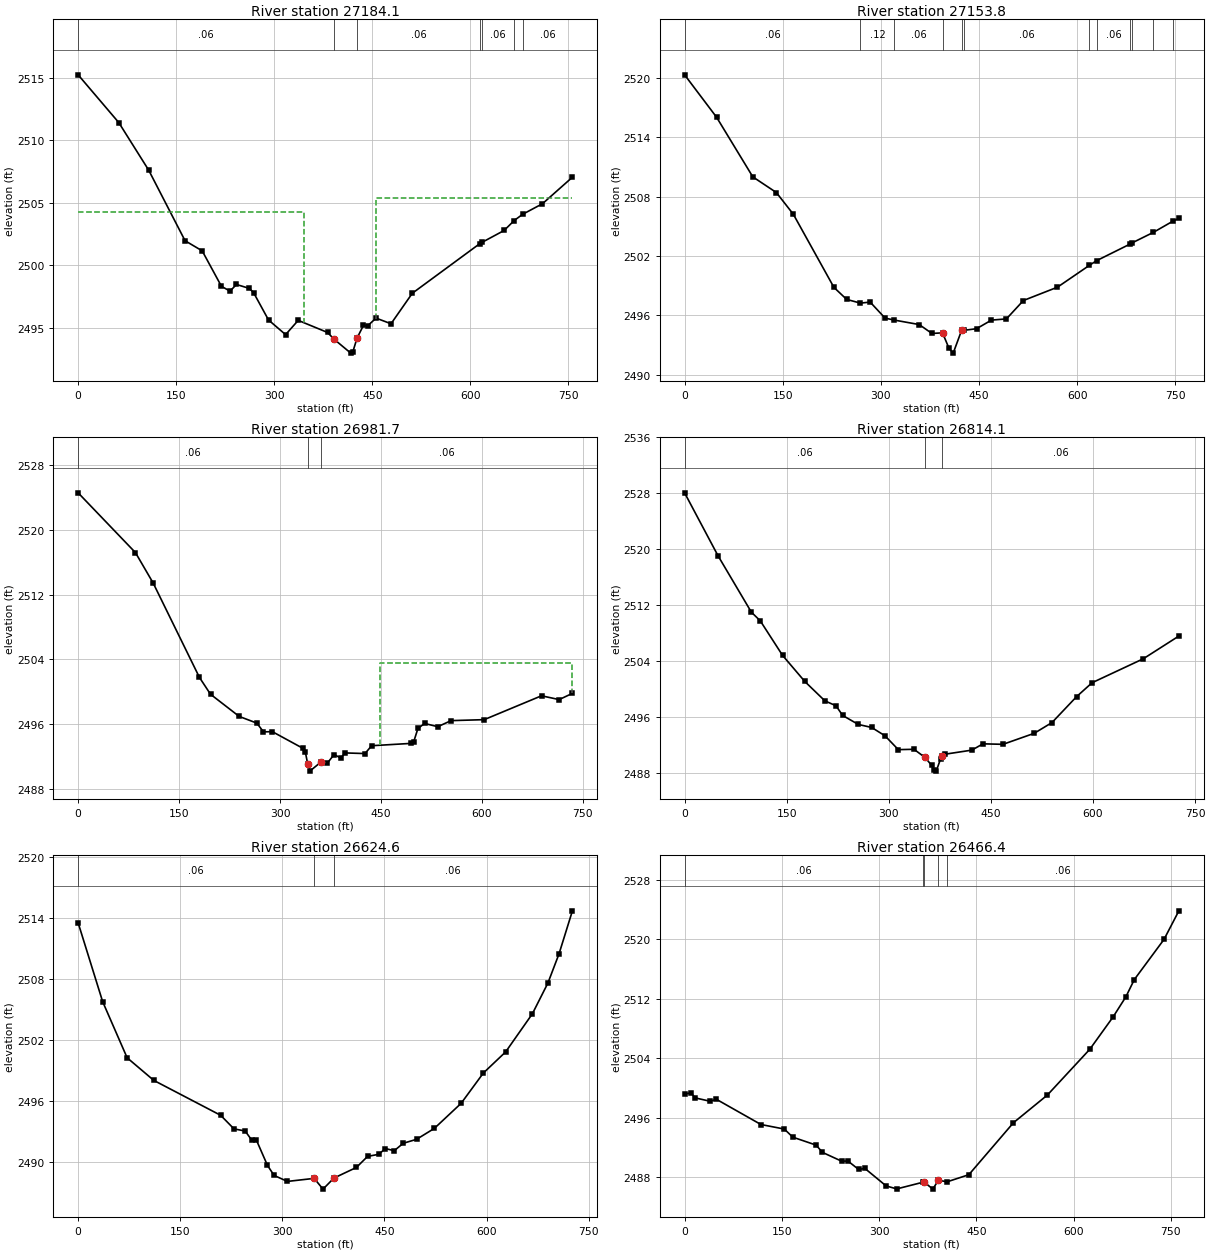
Type RM Length L Ch R = 1 ,27184.1 ,30.8,30.3,30.8
XS GIS Cut Line= 4
     2159260.743      209635.181     2159030.274      209848.723
     2158922.201      209924.243     2158681.316      210119.556
#Sta/Elev= 30
       0 2515.22    62.2  2511.4     108 2507.59   163.6 2501.95   189.8 2501.14
   219.3  2498.3   232.4 2497.92   242.2 2498.45   261.8 2498.14   268.4  2497.8
   291.3 2495.61   317.4 2494.44   336.7 2495.58   381.7 2494.61   391.4 2494.08
   417.1 2492.96   420.3 2493.07   426.7 2494.16   436.4 2495.17   442.8 2495.14
   455.8 2495.76   478.7 2495.31   511.3 2497.75  614.422501.714  618.142501.826
   651.7 2502.77  667.172503.566     6802504.063   710.4 2504.91   756.2 2507.03
#Mann= 7 ,-1 , 0
       0     .06       0   391.4    .045       0   426.7     .06       0
  614.42     .12       0  618.14     .06       0  667.17     .12       0
     680     .06       0
#XS Ineff= 2 , 0
          345.02 2504.27  454.98         2505.38
Permanent Ineff=
       F       F
Bank Sta=391.4,426.7
XS Rating Curve= 0 ,0
Exp/Cntr=0.3,0.1

Type RM Length L Ch R = 1 ,27153.8 ,170,172.1,173.4
XS GIS Cut Line= 4
     2159238.607      209606.535     2158997.722      209835.702
     2158896.159      209906.014     2158666.993      210098.723
#Sta/Elev= 30
       0 2520.32    48.9 2516.03   104.3    2510   140.2 2508.42   166.2 2506.22
   228.2 2498.83   247.7 2497.61  268.742497.238   283.6 2497.34   306.4 2495.72
  320.61 2495.52   358.5 2495.07     378 2494.17   394.2 2494.23     404 2492.68
   410.5 2492.18   423.5 2494.51  427.672494.491   446.2 2494.65     469 2495.52
   491.8 2495.64   517.8  2497.5   569.9 2498.85  618.562501.053  629.622501.527
  680.842503.209  684.03 2503.33  716.482504.393  746.922505.547   755.4  2505.8
#Mann= 12 ,-1 , 0
       0     .06       0  268.74     .12       0  320.61     .06       0
   394.2    .045       0   423.5     .12       0  427.67     .06       0
  618.56     .12       0  629.62     .06       0  680.84     .12       0
  684.03     .06       0  716.48     .12       0  746.92     .06       0
Bank Sta=394.2,423.5
XS Rating Curve= 0 ,0
Exp/Cntr=0.3,0.1

Type RM Length L Ch R = 1 ,26981.7 ,169.5,167.6,165.3
XS GIS Cut Line= 2
     2159170.899      209533.618     2158549.805      209925.546
#Sta/Elev= 30
       0 2524.58    85.2 2517.19   111.5 2513.43   180.3 2501.76   196.7 2499.69
   239.3 2496.95   265.6 2496.12   275.4 2495.04   288.5 2495.07   334.4 2492.99
   337.7  2492.5     341 2491.12   344.3 2490.19   360.6  2491.3   370.5  2491.2
   380.3 2492.24   390.2 2491.81   396.7 2492.44   426.2 2492.36   436.1 2493.33
   495.1 2493.62   498.4 2493.77   504.9 2495.47   514.8 2496.08   534.4 2495.68
   554.1 2496.43   603.3 2496.55   688.5  2499.5   714.7 2499.03   734.4  2499.8
#Mann= 3 ,-1 , 0
       0     .06       0     341    .045       0   360.6     .06       0
#XS Ineff= 2 , 0
                          447.92         2503.53
Permanent Ineff=
       F       F
Bank Sta=341,360.6
XS Rating Curve= 0 ,0
Exp/Cntr=0.3,0.1

Type RM Length L Ch R = 1 ,26814.1 ,190.3,189.6,186.9
XS GIS Cut Line= 2
     2159059.045       209386.67     2158467.774      209808.358
#Sta/Elev= 30
       0 2528.06    49.1 2519.07    98.1 2511.01   111.2 2509.77   143.9 2504.84
   176.6 2501.11   206.1 2498.34   222.4 2497.64   232.3 2496.25   255.2 2494.97
   274.8 2494.54   294.4 2493.35     314 2491.37     337 2491.42   353.3 2490.25
   363.1 2489.11   366.4 2488.44   369.7  2488.3   376.2 2490.08   378.5 2490.39
   382.8 2490.72     422  2491.3   438.4  2492.2   467.8 2492.13   513.6  2493.7
   539.8 2495.24   575.8 2498.93   598.7 2500.93   673.9 2504.35   726.2  2507.6
#Mann= 3 ,-1 , 0
       0     .06       0   353.3    .045       0   378.5     .06       0
Bank Sta=353.3,378.5
XS Rating Curve= 0 ,0
Exp/Cntr=0.3,0.1

Type RM Length L Ch R = 1 ,26624.6 ,159.2,158.1,156.6
XS GIS Cut Line= 2
     2158950.972      209248.649     2158359.701      209670.337
#Sta/Elev= 30
       0 2513.55      36 2505.78      72 2500.24   111.2 2498.01   209.4 2494.57
     229 2493.23   245.4 2493.02   255.2 2492.11   261.7 2492.16   278.1 2489.64
   287.9 2488.64   307.5 2488.05   346.8 2488.35   359.8 2487.29   375.8 2488.38
   408.9 2489.43   425.3 2490.52   441.6 2490.72   451.4 2491.29   464.5 2491.08
   477.6 2491.81   497.2  2492.2   523.4 2493.28   562.7 2495.75   595.4 2498.74
   628.1 2500.82   667.4 2504.58   690.2 2507.61   706.6  2510.5   726.2 2514.73
#Mann= 3 ,-1 , 0
       0     .06       0   346.8    .045       0   375.8     .06       0
Bank Sta=346.8,375.8
XS Rating Curve= 0 ,0
Exp/Cntr=0.3,0.1

Type RM Length L Ch R = 1 ,26466.4 ,205.8,237.9,200.5
XS GIS Cut Line= 2
      2158871.42      209098.723     2158265.951      209562.264
#Sta/Elev= 30
       0 2499.19     9.8 2499.33    16.4 2498.66    39.3 2498.21    49.1 2498.47
   117.8 2495.08   153.8 2494.47   166.9 2493.38   202.9 2492.31   212.7 2491.33
   242.2 2490.15     252 2490.17   268.4 2489.04   278.2 2489.17   310.9 2486.82
   327.3 2486.42  367.732487.318   369.8 2487.33   382.9 2486.39   391.5 2487.59
  404.942487.374   438.5 2488.33   507.3 2495.32   559.6 2499.04   625.1  2505.2
   661.1 2509.56   680.7 2512.25   693.8 2514.58   739.6 2519.98   762.5 2523.82
#Mann= 5 ,-1 , 0
       0     .06       0  367.73     .12       0   369.8    .045       0
   391.5     .12       0  404.94     .06       0
Bank Sta=369.8,391.5
XS Rating Curve= 0 ,0
Exp/Cntr=0.3,0.1

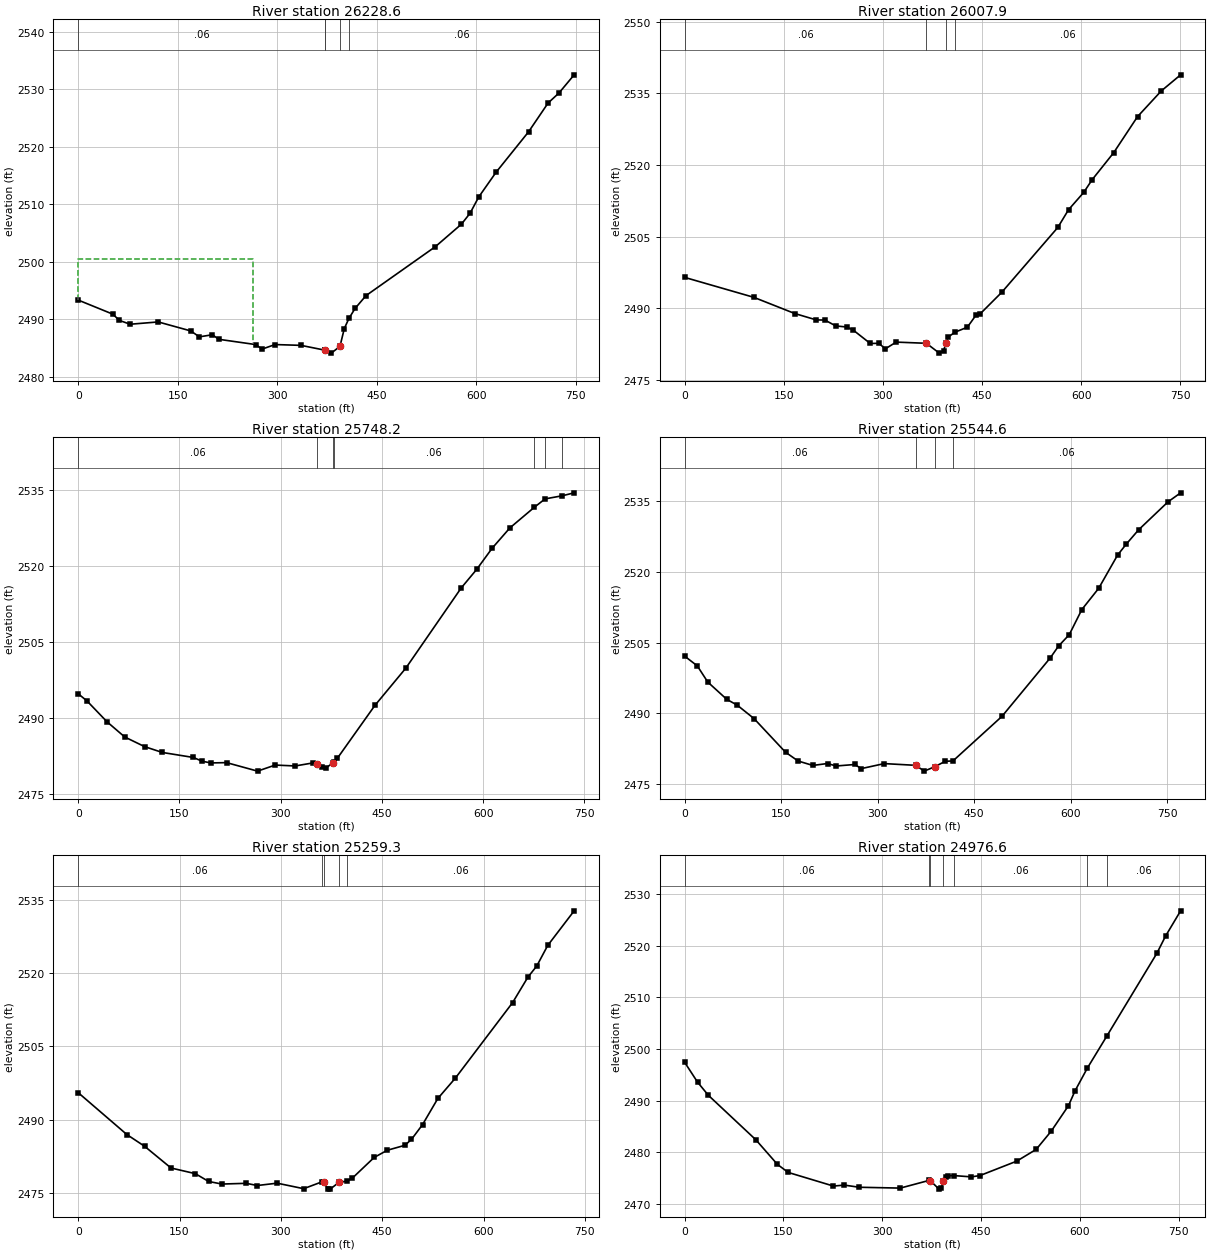
Type RM Length L Ch R = 1 ,26228.6 ,217.3,220.7,210.3
XS GIS Cut Line= 3
      2158755.91      208958.774     2158448.181      209195.133
     2158155.928      209404.558
#Sta/Elev= 30
       0 2493.34    52.2 2490.89      62 2489.81    78.3 2489.14   120.6 2489.54
   169.6 2487.98   182.6 2486.95   202.2 2487.31     212 2486.52   267.4 2485.61
   277.2 2484.82   296.7 2485.61   335.8 2485.47  371.492484.642   371.7 2484.64
   381.5 2484.12   394.6  2485.3   401.1 2488.39  408.232490.182   417.4 2491.89
   433.8 2494.11   538.4 2502.62   577.6 2506.52   590.7 2508.43   603.8 2511.26
   629.9 2515.55   678.9 2522.58   708.3 2527.58   724.7 2529.32   747.6 2532.48
#Mann= 5 ,-1 , 0
       0     .06       0  371.49     .12       0   371.7    .045       0
   394.6     .12       0  408.23     .06       0
#XS Ineff= 2 , 0
           263.3 2500.51
Permanent Ineff=
       F       F
Bank Sta=371.7,394.6
XS Rating Curve= 0 ,0
Exp/Cntr=0.3,0.1

Type RM Length L Ch R = 1 ,26007.9 ,263.8,259.7,252.1
XS GIS Cut Line= 3
     2158618.047      208793.016     2158334.789      209049.489
     2158053.011      209286.949
#Sta/Elev= 30
       0 2496.43   104.5 2492.26   166.6 2488.86   199.2 2487.52   212.3 2487.49
   228.6 2486.26     245 2486.04   254.7 2485.43   280.9 2482.58   293.9 2482.62
   303.7 2481.46   320.1 2482.87   365.8 2482.62   385.4 2480.56   391.9 2481.06
   395.2 2482.62   398.4 2483.88     4092484.942   427.8 2485.99   440.8  2488.5
   447.3  2488.8     480 2493.32   564.7 2506.89     581 2510.62   603.9 2514.23
   616.9 2516.94   649.5  2522.6   685.4 2530.12   721.3  2535.5   750.6 2538.88
#Mann= 4 ,-1 , 0
       0     .06       0   365.8    .045       0   395.2     .12       0
     409     .06       0
Bank Sta=365.8,395.2
XS Rating Curve= 0 ,0
Exp/Cntr=0.3,0.1

Type RM Length L Ch R = 1 ,25748.2 ,206.3,203.6,198.3
XS GIS Cut Line= 2
     2158431.849      208625.203     2157905.753      209138.114
#Sta/Elev= 30
       0 2494.78    13.1 2493.35    42.6 2489.25    68.9 2486.24    98.4 2484.33
   124.6 2483.18   170.6 2482.19   183.7 2481.44   196.8 2481.11   219.8 2481.17
   265.7 2479.49   291.9 2480.69   321.4 2480.51   347.7 2481.11   354.2 2480.81
   360.8 2480.25   367.4 2480.14   377.2 2481.11  378.712481.305   383.8    2482
   439.5 2492.46   485.5 2499.86   567.5  2515.7   590.4 2519.36   613.4 2523.56
   639.6 2527.56  675.882531.641  691.722533.291  717.182533.908   734.8 2534.49
#Mann= 7 ,-1 , 0
       0     .06       0   354.2    .045       0   377.2     .12       0
  378.71     .06       0  675.88     .12       0  691.72     .06       0
  717.18    .016       0
Bank Sta=354.2,377.2
XS Rating Curve= 0 ,0
Exp/Cntr=0.3,0.1

Type RM Length L Ch R = 1 ,25544.6 ,251.1,285.3,255.6
XS GIS Cut Line= 2
     2158303.712      208429.452     2157815.864      209026.674
#Sta/Elev= 30
       0 2502.12    19.6 2500.06    35.9 2496.62    65.4 2492.95    81.7 2491.71
   107.8 2488.86   156.8 2481.71   176.4 2479.84   199.3  2478.9   222.2 2479.31
   235.3 2478.78   264.7  2479.1   274.5 2478.22   310.4 2479.29   359.4 2478.92
   372.5 2477.69   388.8 2478.62   405.2 2479.78  417.212479.857   493.4 2489.33
   568.6 2501.77   581.6 2504.31     598 2506.68   617.6 2512.03   643.7 2516.52
   673.1 2523.58   686.2 2525.85   705.8 2528.96   751.5  2534.9   771.2 2536.83
#Mann= 4 ,-1 , 0
       0     .06       0   359.4    .045       0   388.8     .12       0
  417.21     .06       0
Bank Sta=359.4,388.8
XS Rating Curve= 0 ,0
Exp/Cntr=0.3,0.1

Type RM Length L Ch R = 1 ,25259.3 ,283.4,282.7,280.5
XS GIS Cut Line= 3
     2158112.159      208278.139     2157889.507      208569.258
     2157663.291      208859.109
#Sta/Elev= 30
       0 2495.51      72 2486.93    98.2 2484.53   137.4 2480.07   173.4 2478.91
   193.1 2477.31   212.7 2476.78   248.7 2476.93   265.1 2476.48   294.5 2476.96
   333.8 2475.83  360.682477.227   363.2 2477.18   369.8 2475.82     373 2475.74
     386 2477.13  397.232477.379   405.6 2477.96   438.1 2482.23   457.6 2483.71
   483.6 2484.72   493.4 2485.94   509.7 2488.95   532.4 2494.32   558.5 2498.52
   643.1 2513.97   665.8  2519.2   678.9 2521.48   695.1 2525.69   734.2 2532.78
#Mann= 5 ,-1 , 0
       0     .06       0  360.68     .12       0   363.2    .045       0
     386     .12       0  397.23     .06       0
Bank Sta=363.2,386
XS Rating Curve= 0 ,0
Exp/Cntr=0.3,0.1

Type RM Length L Ch R = 1 ,24976.6 ,226.3,211.4,193.4
XS GIS Cut Line= 2
     2157925.239      208099.591     2157450.582      208684.415
#Sta/Elev= 30
       0 2497.42    19.6 2493.58      36 2491.04   108.1 2482.44   140.8 2477.69
   157.2 2476.13     226 2473.49   242.3 2473.68   265.3 2473.26   327.5  2473.1
  370.66 2474.57   373.3 2474.49   386.4  2472.9   389.7 2473.08     393 2474.42
   396.2  2475.2   399.5  2475.5   408.72475.519   435.6 2475.27   448.6 2475.53
   504.3 2478.31   533.8 2480.58   556.7 2484.11   582.9 2489.04   592.7 2491.87
  611.442496.283  641.532502.579   717.2 2518.52   730.3 2521.83   753.2 2526.72
#Mann= 7 ,-1 , 0
       0     .06       0  370.66     .12       0   373.3    .045       0
     393     .12       0   408.7     .06       0  611.44     .12       0
  641.53     .06       0
Bank Sta=373.3,393
XS Rating Curve= 0 ,0
Exp/Cntr=0.3,0.1

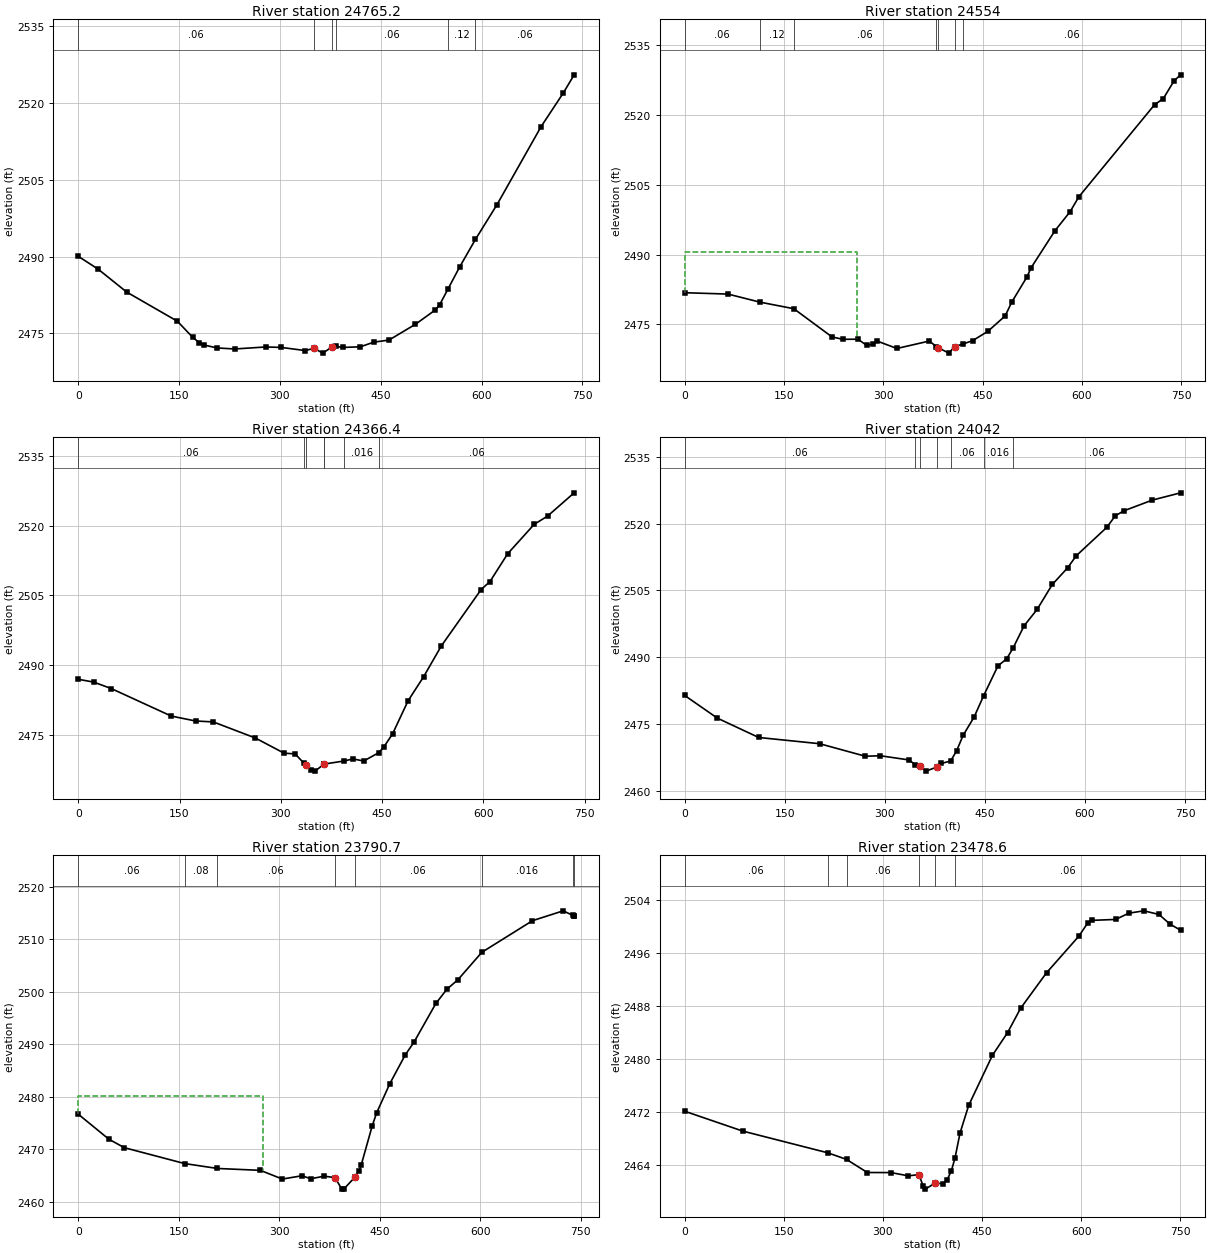
Type RM Length L Ch R = 1 ,24765.2 ,194.6,211.2,212.7
XS GIS Cut Line= 2
     2157609.716      207951.485     2157418.295      208663.827
#Sta/Elev= 30
       0 2490.06    29.5 2487.56    72.1 2483.08   147.5 2477.39   170.5 2474.22
   180.3 2473.18   186.9 2472.76   206.5 2472.18   232.8 2471.98   278.6 2472.37
   301.6 2472.29   337.7 2471.67   350.8 2472.12   363.7 2471.17     377 2472.33
  382.762472.503   393.4 2472.28   419.6  2472.4   439.3  2473.3   462.2 2473.72
   501.6  2476.8   531.1 2479.59   537.6 2480.62  550.152483.718   567.1 2487.93
  590.872493.369   622.9 2500.14   688.4 2515.34   721.2 2521.86   737.6 2525.45
#Mann= 6 ,-1 , 0
       0     .06       0   350.8    .045       0     377     .12       0
  382.76     .06       0  550.15     .12       0  590.87     .06       0
Bank Sta=350.8,377
XS Rating Curve= 0 ,0
Exp/Cntr=0.3,0.1

Type RM Length L Ch R = 1 ,24554   ,196.4,187.6,161.1
XS GIS Cut Line= 2
     2157479.036      207910.089     2157187.155      208600.078
#Sta/Elev= 30
       0  2481.8    65.4 2481.51  113.56 2479.78  164.872478.363   222.5 2472.31
   238.8 2471.79   261.7 2471.81   274.8 2470.51   284.6 2470.72   291.2 2471.39
   320.6 2469.82   369.7 2471.42  380.292470.198   382.8    2470   399.1 2468.82
   407.8 2470.24  419.782470.746   435.1 2471.51     458  2473.5   484.2 2476.82
     494 2479.76   516.9 2485.15   523.4 2487.18   559.4 2495.13   582.3 2499.22
   595.4  2502.4   709.9 2522.21     723  2523.5   739.4 2527.35   749.2 2528.62
#Mann= 7 ,-1 , 0
       0     .06       0  113.56     .12       0  164.87     .06       0
  380.29     .12       0   382.8    .045       0   407.8     .12       0
  419.78     .06       0
#XS Ineff= 2 , 0
          260.28 2490.45
Permanent Ineff=
       F       F
Bank Sta=382.8,407.8
XS Rating Curve= 0 ,0
Exp/Cntr=0.3,0.1

Type RM Length L Ch R = 1 ,24366.4 ,255.3,324.4,308.9
XS GIS Cut Line= 2
     2157237.739      207850.459     2157123.156      208575.719
#Sta/Elev= 30
       0 2486.97      23 2486.36    49.2 2484.96   137.7 2479.07   173.7 2478.01
     200 2477.81   262.2 2474.36   304.8  2471.1   321.2 2470.94  334.212468.936
   337.6 2468.58   344.2 2467.56   350.7 2467.24   363.8 2468.73  364.122468.759
  394.022469.423   406.5 2469.86   422.8 2469.42  444.87 2471.19   452.4  2472.4
   465.5 2475.26   488.4 2482.35   511.4 2487.51   537.6 2494.13   596.6 2506.25
   609.7 2507.97   635.9 2513.94   675.2 2520.26   694.9 2522.02   734.3 2527.02
#Mann= 7 ,-1 , 0
       0     .06       0  334.21     .12       0   337.6    .045       0
   363.8     .12       0  364.12     .06       0  394.02    .016       0
  444.87     .06       0
Bank Sta=337.6,363.8
XS Rating Curve= 0 ,0
Exp/Cntr=0.3,0.1

Type RM Length L Ch R = 1 ,24042   ,241.1,251.3,260
XS GIS Cut Line= 3
     2157120.307      207830.569     2156957.068      208168.135
     2156793.446      208497.989
#Sta/Elev= 30
       0 2481.39    48.9  2476.3   110.9 2471.95   202.2 2470.55   270.6 2467.74
   293.4 2467.84   335.8 2466.91  345.682465.845   352.1 2465.56   361.9 2464.39
   378.6 2465.37   384.7 2466.11  398.582466.671   407.6 2468.98   417.3 2472.45
   433.6  2476.5  448.182481.374   469.5 2488.06   482.5  2489.6  492.362492.107
   508.6 2497.03   528.1  2500.7   550.9 2506.32   573.7 2510.03   586.8 2512.77
   632.4 2519.13   645.4 2521.76   658.4 2522.88   700.8 2525.28   743.2 2526.91
#Mann= 7 ,-1 , 0
       0     .06       0  345.68     .12       0   352.1    .045       0
   378.6     .12       0  398.58     .06       0  448.18    .016       0
  492.36     .06       0
Bank Sta=352.1,378.6
XS Rating Curve= 0 ,0
Exp/Cntr=0.3,0.1

Type RM Length L Ch R = 1 ,23790.7 ,316.3,312.2,311.2
XS GIS Cut Line= 2
     2156964.302      207731.969      2156570.66      208358.743
#Sta/Elev= 30
       0 2476.71    45.8 2471.93    68.8 2470.32  158.772467.292  207.852466.358
   271.8    2466   304.6 2464.34     334 2464.97   347.1 2464.39   366.8 2464.89
   383.2 2464.62     393  2462.5   396.3 2462.42   412.6 2464.66   419.2 2465.89
   422.5  2467.1   438.8  2474.5   445.4 2476.97     465 2482.52     488 2487.99
   501.1 2490.43   533.8 2497.82   550.2 2500.52   566.6 2502.32  602.292507.552
   677.9 2513.58   723.8 2515.46  737.692514.613  739.562514.479   740.1 2514.44
#Mann= 8 ,-1 , 0
       0     .06       0  158.77     .08       0  207.85     .06       0
   383.2    .045       0   412.6     .06       0  602.29    .016       0
  737.69     .06       0  739.56     .12       0
#XS Ineff= 2 , 0
          275.41 2480.13
Permanent Ineff=
       F       F
Bank Sta=383.2,412.6
XS Rating Curve= 0 ,0
Exp/Cntr=0.3,0.1

Type RM Length L Ch R = 1 ,23478.6 ,286.2,366,269.1
XS GIS Cut Line= 3
      2156687.48      207553.734     2156530.327      207889.524
     2156334.425      208214.724
#Sta/Elev= 30
       0 2472.06    87.8 2469.06  216.582465.776  244.89 2464.78   276.4  2462.8
   312.2 2462.79   338.2  2462.3   354.5 2462.48     361  2460.7   364.2 2460.29
   378.2 2461.16   390.4 2461.14   396.9 2461.64   403.5 2463.06  408.99 2464.98
   416.6 2468.75   429.7 2472.94   465.7 2480.52   488.6 2483.94   508.2  2487.6
   547.5 2492.98   596.6 2498.53   609.7 2500.49   616.2  2500.9   652.2 2501.04
   671.8 2501.98   694.8 2502.34   717.7 2501.79     734 2500.36   750.4  2499.4
#Mann= 6 ,-1 , 0
       0     .06       0  216.58     .07       0  244.89     .06       0
   354.5    .045       0   378.2     .12       0  408.99     .06       0
Bank Sta=354.5,378.2
XS Rating Curve= 0 ,0
Exp/Cntr=0.3,0.1

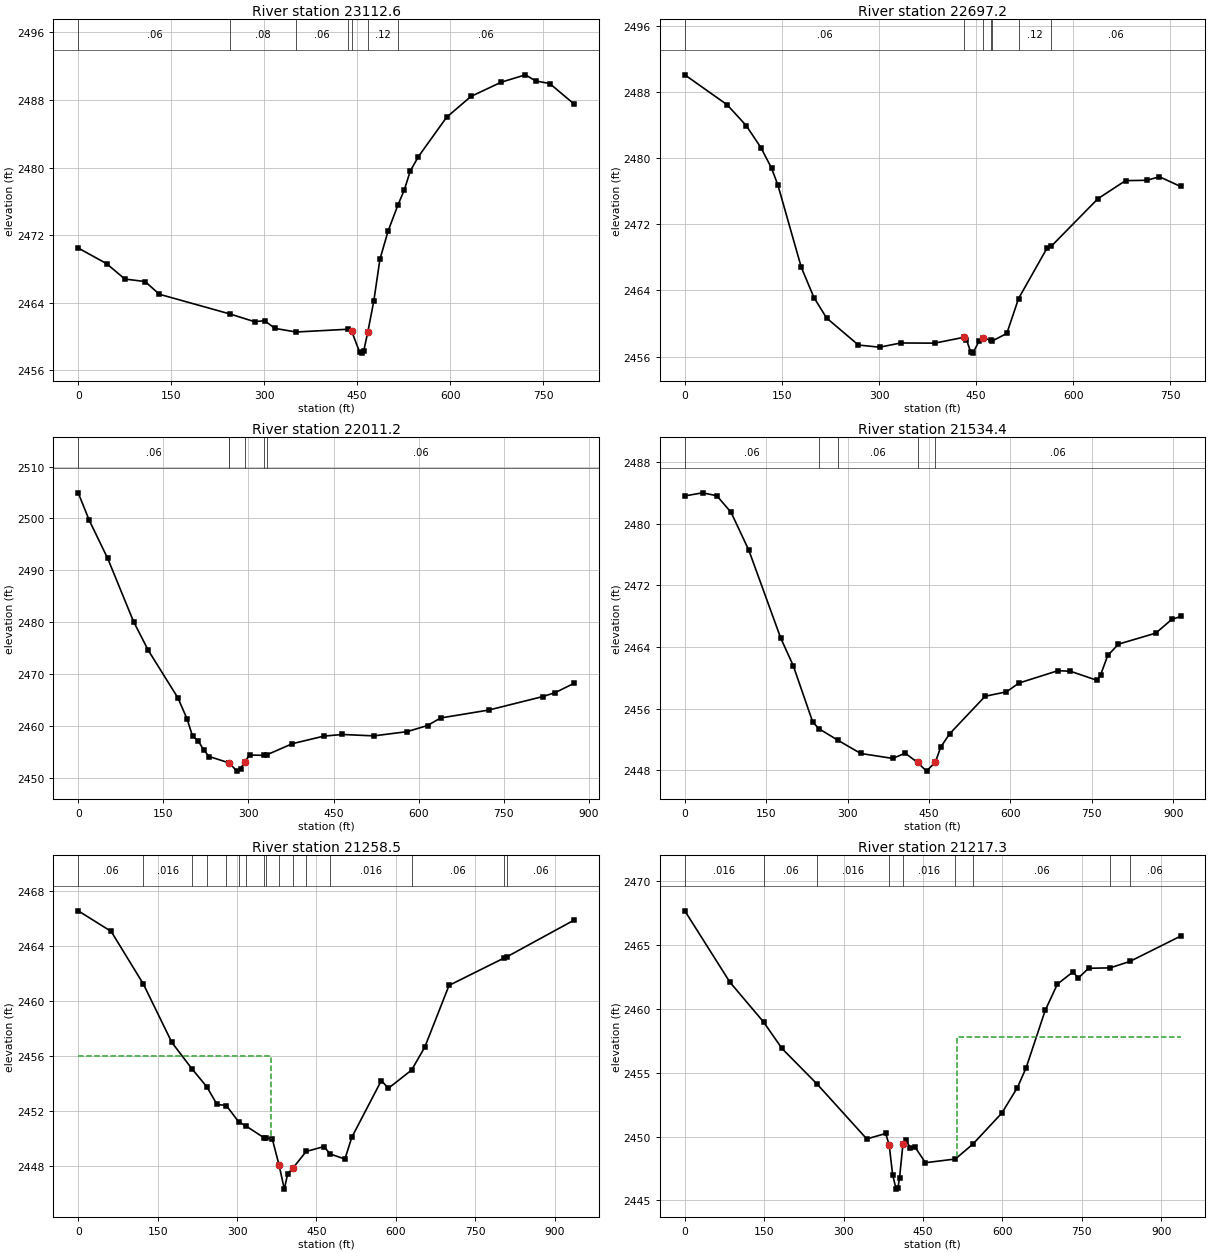
Type RM Length L Ch R = 1 ,23112.6 ,383.1,415.4,365.4
XS GIS Cut Line= 3
     2156654.406      207512.785     2156404.406      207610.007
      2156114.22      208055.343
#Sta/Elev= 30
       0 2470.47    45.8 2468.62    75.2  2466.8     108  2466.5   130.8    2465
  245.582462.649   284.5 2461.75   300.8 2461.87   317.2 2460.96  351.39 2460.53
  435.292460.857   441.1 2460.64   454.1 2458.11   457.4 2458.03   460.6 2458.29
   467.2 2460.54   476.9 2464.23   486.7 2469.13   499.8 2472.46  516.022475.613
   525.9 2477.31   535.6 2479.58   548.7 2481.28   594.3 2485.95   633.5 2488.41
   682.4  2490.1   721.5 2490.97   737.8 2490.25   760.6 2489.94   799.8 2487.52
#Mann= 7 ,-1 , 0
       0     .06       0  245.58     .08       0  351.39     .06       0
  435.29     .12       0   441.1    .045       0   467.2     .12       0
  516.02     .06       0
Bank Sta=441.1,467.2
XS Rating Curve= 0 ,0
Exp/Cntr=0.3,0.1

Type RM Length L Ch R = 1 ,22697.2 ,552.3,686,577.7
XS GIS Cut Line= 3
     2156319.337      207233.271      2156152.67       207394.73
     2155834.962      207823.549
#Sta/Elev= 30
       0 2490.13    65.4  2486.5    94.8 2483.98   117.7 2481.29     134 2478.81
   143.8 2476.76   179.8 2466.82   199.4 2463.15     219 2460.66   268.1 2457.39
   300.8 2457.13   333.6 2457.64   385.9 2457.62   431.8 2458.34     435 2458.04
   441.6 2456.51   444.9 2456.41   454.7 2457.92   460.1 2458.26  473.382457.952
  475.12 2457.89   497.3  2458.8   515.42463.023   559.5 2469.15  565.892469.358
     638 2475.12   680.6 2477.31   713.4 2477.35     733 2477.78   765.7  2476.6
#Mann= 7 ,-1 , 0
       0     .06       0   431.8    .045       0   460.1     .06       0
  473.38     .12       0  475.12     .06       0   515.4     .12       0
  565.89     .06       0
Bank Sta=431.8,460.1
XS Rating Curve= 0 ,0
Exp/Cntr=0.3,0.1

Type RM Length L Ch R = 1 ,22011.2 ,479.6,476.8,469.2
XS GIS Cut Line= 3
     2155982.097      206922.073     2155832.791      207236.309
      2155659.18      207732.837
#Sta/Elev= 30
       0 2504.95    19.5 2499.63      52 2492.29    97.5 2480.13   123.6 2474.55
   175.6 2465.43   191.8 2461.35   201.6    2458   211.3 2457.15   221.1 2455.36
   230.8 2454.09  266.312452.844   266.6 2452.83   279.6 2451.27   286.1 2451.74
   293.4 2453.06   302.4 2454.38  326.722454.314  332.552454.417   377.3 2456.56
   432.8 2458.02   465.5 2458.34   521.1 2458.07   579.9 2458.89   615.8 2460.07
   638.7 2461.52   723.6 2463.05   818.4 2465.64   841.2 2466.43   873.9 2468.21
#Mann= 6 ,-1 , 0
       0     .06       0  266.31     .12       0   266.6    .045       0
   293.4     .06       0  326.72     .12       0  332.55     .06       0
Bank Sta=266.6,293.4
XS Rating Curve= 0 ,0
Exp/Cntr=0.3,0.1

Type RM Length L Ch R = 1 ,21534.4 ,259.5,275.9,290.2
XS GIS Cut Line= 2
     2155552.409      206736.743     2155326.715       207622.16
#Sta/Elev= 30
       0 2483.62    32.8 2484.02      59 2483.64    85.2 2481.49   117.9 2476.58
   176.8 2465.16   199.8 2461.59   235.8 2454.26  247.462453.388   281.72451.926
   324.2 2450.19   383.2 2449.55   406.1 2450.23     429 2449.02   445.4  2447.9
   461.8 2449.08   471.6 2451.02     488 2452.74   553.5 2457.62   592.8 2458.19
   615.7 2459.33   687.8 2460.94   710.7 2460.86   759.8 2459.68   766.4 2460.43
   779.4 2462.91   799.1 2464.38   867.9 2465.81   897.4 2467.59   913.7 2467.97
#Mann= 5 ,-1 , 0
       0     .06       0  247.46     .08       0   281.7     .06       0
     429    .045       0   461.8     .06       0
Bank Sta=429,461.8
XS Rating Curve= 0 ,0
Exp/Cntr=0.3,0.1

Type RM Length L Ch R = 1 ,21258.5 ,41.3,41.2,43.5
XS GIS Cut Line= 4
      2155433.84      206686.435     2155314.128      206941.605
     2155218.642      207061.396     2154775.934      207297.507
#Sta/Elev= 30
       0 2466.57    62.3 2465.07  123.152461.235     177 2456.98  214.632455.076
  243.252453.739   262.2 2452.47  279.882452.388  302.942451.212  317.34 2450.89
  350.34 2450.06  355.11 2450.03   366.6 2449.97   379.6 2448.04   389.4  2446.3
   395.9 2447.43   405.7 2447.83  430.652449.043   464.6  2449.4  475.642448.866
   503.9 2448.49     517 2450.08   572.8 2454.21   585.9 2453.64  629.932454.972
   654.8 2456.64   700.7 2461.14  804.282463.126  810.422463.231   936.8 2465.89
#Mann= 16 ,-1 , 0
       0     .06       0  123.15    .016       0  214.63     .12       0
  243.25    .016       0  279.88     .12       0  302.94    .016       0
  317.34     .06       0  350.34    .016       0  355.11     .06       0
   379.6    .045       0   405.7    .016       0  430.65     .12       0
  475.64    .016       0  629.93     .06       0  804.28     .12       0
  810.42     .06       0
#XS Ineff= 2 , 0
          364.44 2456.03
Permanent Ineff=
       F       F
Bank Sta=379.6,405.7
XS Rating Curve= 0 ,0
Exp/Cntr=0.3,0.1

Type RM Length L Ch R = 1 ,21217.3 ,265.4,268.3,267.3
XS GIS Cut Line= 4
     2155406.062      206655.185      2155286.35      206910.355
     2155190.864      207030.146     2154748.156      207266.257
#Sta/Elev= 30
       0 2467.68    85.2 2462.09  148.932458.966   183.5  2456.9  250.112454.102
   343.8 2449.81   379.6 2450.24   386.2 2449.31   392.7    2447   399.2 2445.88
   402.4 2445.93   405.7 2446.75   412.2 2449.43   418.8  2449.7   425.3 2449.14
     435 2449.17   454.7 2447.95  511.112448.239  544.592449.419     599 2451.84
   628.5 2453.84   644.9 2455.39     681 2459.89     704 2461.94   733.5  2462.9
   743.3 2462.41     763 2463.18  803.632463.212  840.872463.715   936.8  2465.7
#Mann= 9 ,-1 , 0
       0    .016       0  148.93     .06       0  250.11    .016       0
   386.2    .045       0   412.2    .016       0  511.11     .12       0
  544.59     .06       0  803.63     .12       0  840.87     .06       0
#XS Ineff= 2 , 0
                           514.5         2457.76
Permanent Ineff=
       F       F
Bank Sta=386.2,412.2
XS Rating Curve= 0 ,0
Exp/Cntr=0.3,0.1

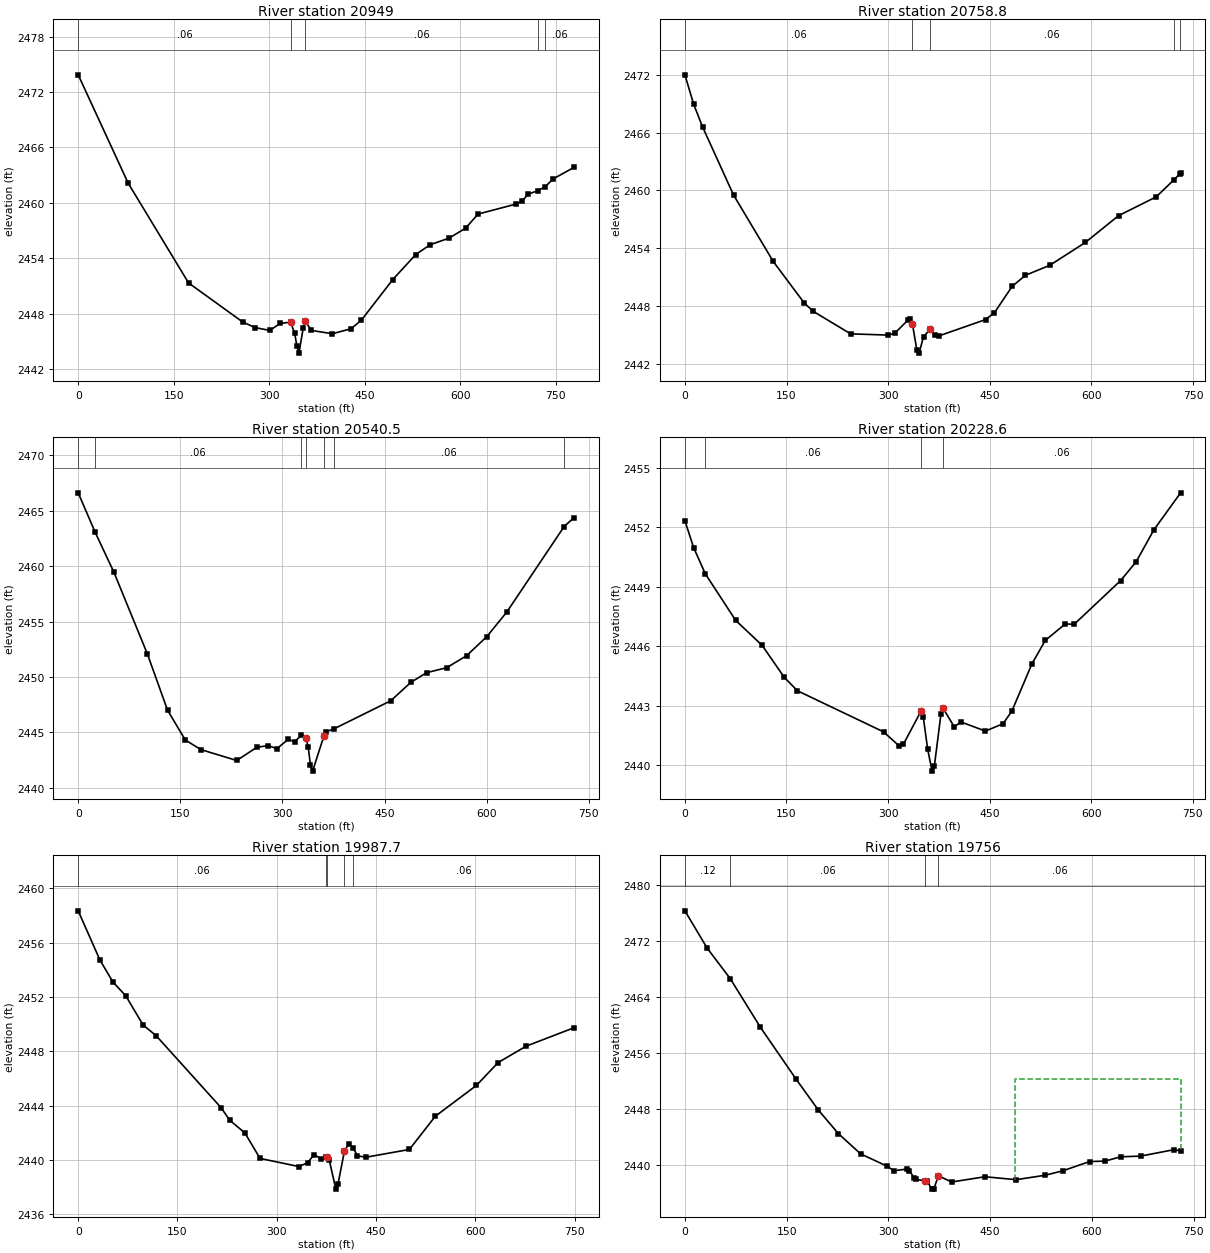
Type RM Length L Ch R = 1 ,20949   ,196.3,190.2,183.5
XS GIS Cut Line= 2
     2155237.739      206583.966     2154718.642      207163.827
#Sta/Elev= 30
       0 2473.87    78.5 2462.13   173.3 2451.33   258.3  2447.1     278 2446.49
   300.8 2446.19   317.2 2446.95   333.5 2447.08   339.9 2445.87   343.4 2444.47
   346.6 2443.73   353.2 2446.43   356.4 2447.19   366.2 2446.19   398.9 2445.83
   428.4 2446.37   444.7 2447.31   493.8 2451.69   529.8  2454.4   552.6 2455.47
   582.1 2456.18   608.2 2457.26   627.8 2458.79   686.7 2459.86   696.5 2460.16
   706.3 2460.94  721.242461.316  733.032461.734   745.6  2462.6   778.3 2463.84
#Mann= 5 ,-1 , 0
       0     .06       0   333.5    .045       0   356.4     .06       0
  721.24     .12       0  733.03     .06       0
Bank Sta=333.5,356.4
XS Rating Curve= 0 ,0
Exp/Cntr=0.3,0.1

Type RM Length L Ch R = 1 ,20758.8 ,221.6,218.4,214.1
XS GIS Cut Line= 3
     2155053.622      206435.626     2154851.736      206743.938
     2154650.266      207046.138
#Sta/Elev= 30
       0 2471.99      13 2468.93    26.1 2466.59    71.8 2459.53   130.4 2452.64
   176.1 2448.34   189.2 2447.48   244.6 2445.14     300 2445.01   309.8  2445.2
   329.4 2446.58   332.7 2446.66   335.9 2446.15   342.4 2443.43   345.7 2443.14
   352.2 2444.84     362 2445.62   368.5 2445.01   375.1 2444.93   443.8 2446.62
   456.9 2447.33     483 2450.06   502.7 2451.21   538.7 2452.25     591 2454.61
   640.1 2457.39   695.7 2459.34  721.882461.108  730.632461.727   731.7 2461.77
#Mann= 5 ,-1 , 0
       0     .06       0   335.9    .045       0     362     .06       0
  721.88     .12       0  730.63     .06       0
Bank Sta=335.9,362
XS Rating Curve= 0 ,0
Exp/Cntr=0.3,0.1

Type RM Length L Ch R = 1 ,20540.5 ,309.3,311.9,314.6
XS GIS Cut Line= 3
     2154844.777      206297.623     2154678.347      206621.366
       2154510.2      206944.263
#Sta/Elev= 30
       0 2466.61   25.012463.037    52.5 2459.44   101.7 2452.06   131.2    2447
   157.4  2444.3   180.4 2443.44   232.8 2442.46   262.4 2443.65   278.8  2443.8
   291.9 2443.53   308.3 2444.36   318.1 2444.16   327.52444.725   334.5 2444.49
   337.8 2443.68   341.1 2442.06   344.3  2441.5   360.7 2444.64     364 2445.05
  375.722445.317   459.1 2447.85   488.6 2449.51   511.6 2450.38   541.1 2450.83
   570.6 2451.92   600.2 2453.64   629.7 2455.87  713.692463.567   728.1 2464.37
#Mann= 7 ,-1 , 0
       0     .12       0   25.01     .06       0   327.5     .12       0
   334.5    .045       0   360.7     .12       0  375.72     .06       0
  713.69     .12       0
Bank Sta=334.5,360.7
XS Rating Curve= 0 ,0
Exp/Cntr=0.3,0.1

Type RM Length L Ch R = 1 ,20228.6 ,244.6,240.9,235.2
XS GIS Cut Line= 3
     2154608.201       206137.96     2154419.355      206454.265
     2154225.441      206762.056
#Sta/Elev= 30
       0 2452.32      13 2450.96   30.162449.648      75  2447.3   114.1 2446.04
   146.7 2444.43   166.3 2443.75   293.4 2441.68   316.2 2440.98   322.8 2441.06
   348.8 2442.73   352.1 2442.42   358.6  2440.8   365.1  2439.7   368.4 2439.94
   378.2 2442.58   381.5 2442.86   397.9 2441.93   407.7 2442.18   443.8 2441.72
     470 2442.09   483.1 2442.74   512.6 2445.11   532.3 2446.29   561.8 2447.12
   574.9  2447.1   643.7 2449.31   666.6 2450.26   692.8 2451.87   732.2 2453.73
#Mann= 4 ,-1 , 0
       0     .12       0   30.16     .06       0   348.8    .045       0
   381.5     .06       0
Bank Sta=348.8,381.5
XS Rating Curve= 0 ,0
Exp/Cntr=0.3,0.1

Type RM Length L Ch R = 1 ,19987.7 ,228.4,231.7,233.7
XS GIS Cut Line= 2
     2154374.892      205986.743     2154062.392      206667.299
#Sta/Elev= 30
       0 2458.35    32.7 2454.74    52.3 2453.12    71.9 2452.09    98.1 2449.94
   117.7 2449.16   215.8 2443.86   228.9 2442.93   251.8    2442   274.7 2440.12
   333.6 2439.52   346.6 2439.81   356.4  2440.4   366.3 2440.11  374.372440.261
   376.1 2440.24   379.3 2439.99   389.2 2437.86   392.4 2438.21   402.2 2440.66
   408.8  2441.2  415.682440.875   421.8 2440.31   434.9 2440.21   500.3 2440.78
   539.6 2443.23   601.7  2445.5   634.4 2447.18   676.9 2448.39   748.9 2449.74
#Mann= 5 ,-1 , 0
       0     .06       0  374.37     .12       0   376.1    .045       0
   402.2     .12       0  415.68     .06       0
Bank Sta=376.1,402.2
XS Rating Curve= 0 ,0
Exp/Cntr=0.3,0.1

Type RM Length L Ch R = 1 ,19756   ,321.9,316.8,309.8
XS GIS Cut Line= 2
     2154185.537      205920.325     2153832.227      206560.097
#Sta/Elev= 30
       0 2476.36    32.8 2471.03    66.82466.674   111.4  2459.7   163.9  2452.3
   196.6  2447.9   226.1 2444.53   258.9 2441.63   298.2 2439.85   308.1 2439.21
   327.7 2439.45     331 2439.24   337.6 2438.22   340.8 2437.96     354 2437.78
   357.2 2437.72   363.8 2436.58   367.1 2436.62   373.6 2438.49   393.3  2437.6
   442.4 2438.35   488.3 2437.93   530.9 2438.56   557.2  2439.2   596.5 2440.52
   619.4 2440.59   642.4  2441.2   671.8  2441.3     721 2442.22   730.8 2442.05
#Mann= 4 ,-1 , 0
       0     .12       0    66.8     .06       0     354    .045       0
   373.6     .06       0
#XS Ineff= 2 , 0
                          486.25         2452.26
Permanent Ineff=
       F       F
Bank Sta=354,373.6
XS Rating Curve= 0 ,0
Exp/Cntr=0.3,0.1