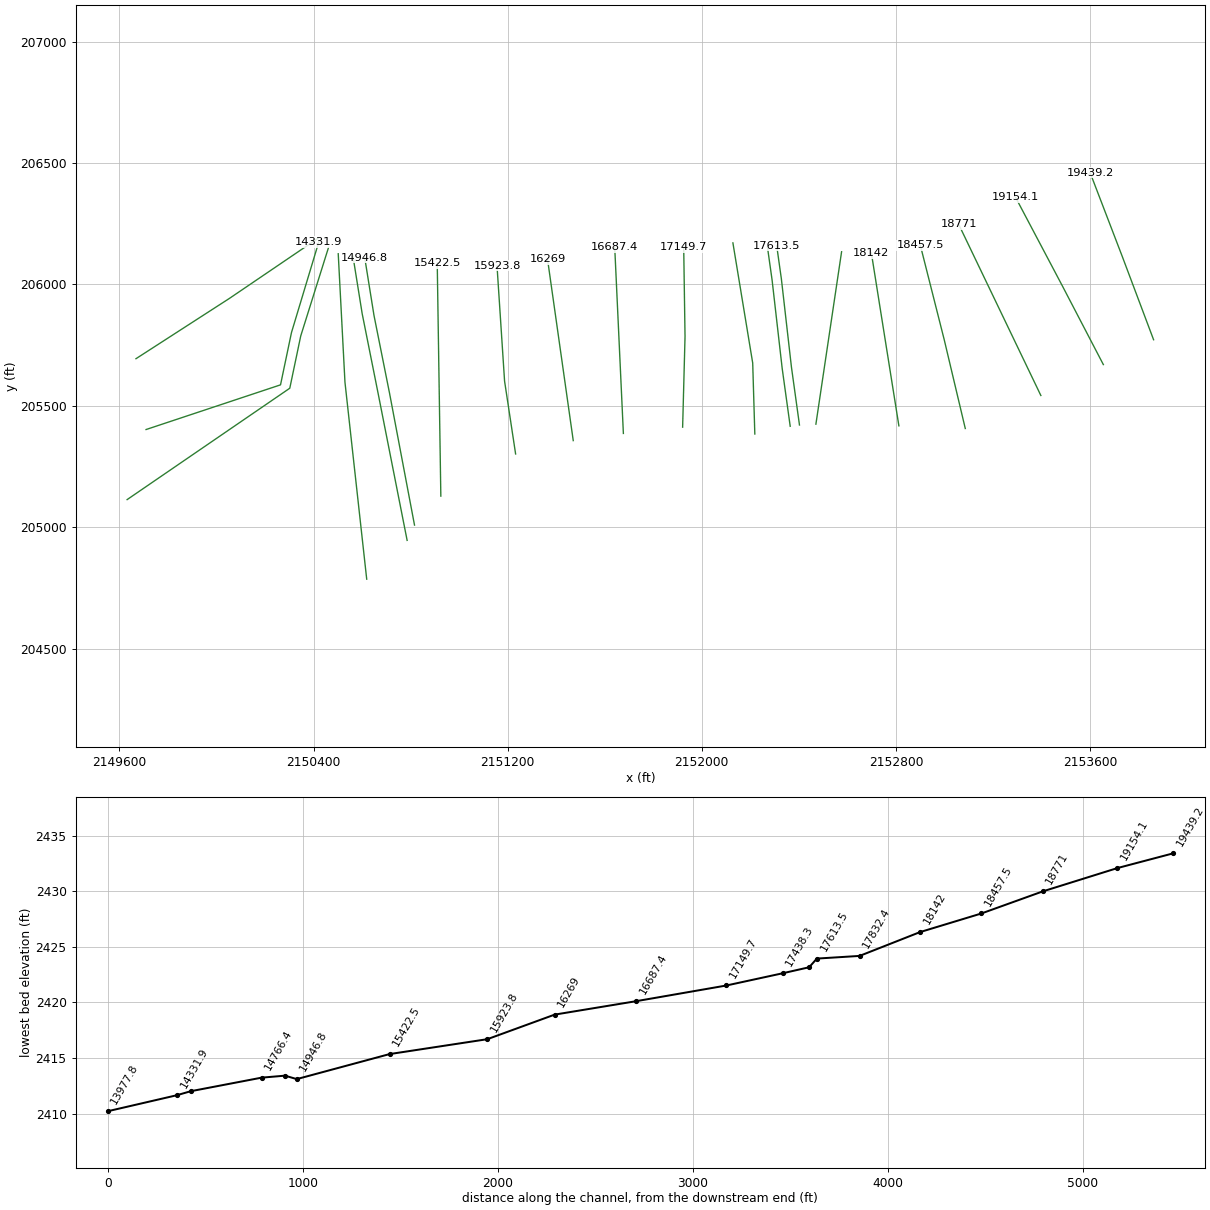
HEC-RAS study KITCHENCK.prj: KITCHENCK

--- KITCHENCK.g01 (geometry) --- (continued)

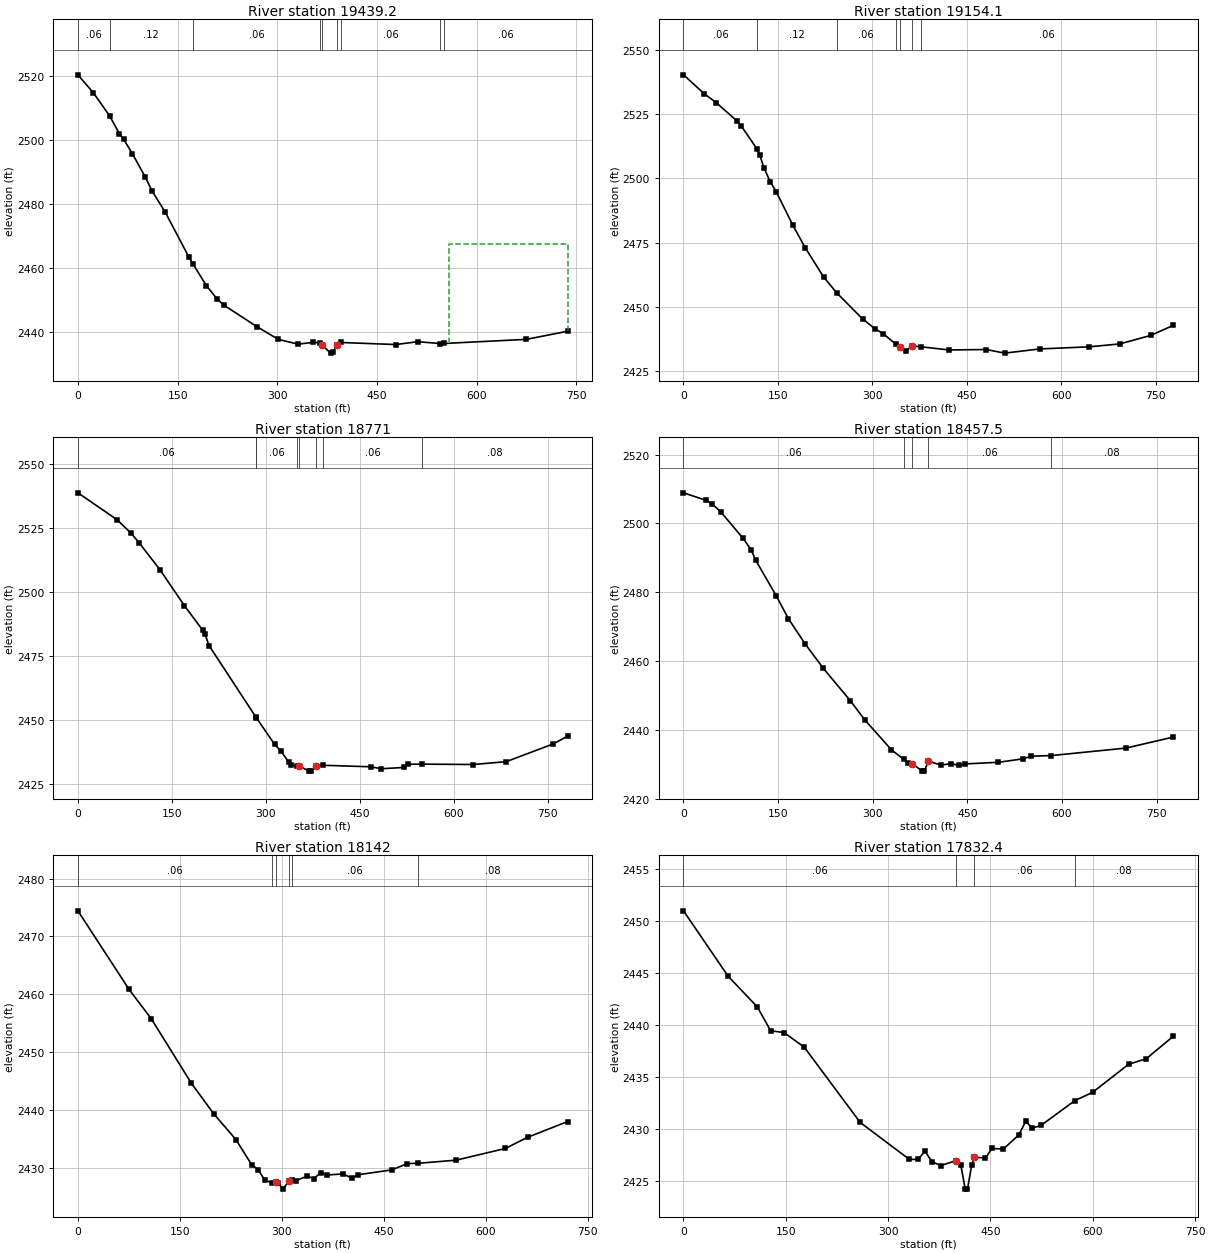
Type RM Length L Ch R = 1 ,19439.2 ,278.8,285.1,289.3
XS GIS Cut Line= 3
     2153862.045      205771.959     2153733.844       206112.58
     2153600.256      206460.549
#Sta/Elev= 30
       0 2520.26      23 2514.72   47.55 2507.51    62.3 2501.92    68.9  2500.1
      82 2495.66   101.6 2488.24   111.5 2484.03   131.2 2477.46   167.2 2463.29
  173.462461.095   193.4 2454.43   209.8  2450.2   219.7 2448.37   268.9 2441.71
   301.6 2437.68   331.2 2436.21   354.1 2436.76  363.982436.611   367.2 2435.89
   380.3  2433.4   383.6 2433.75   390.1 2435.93  395.62 2436.72   478.4 2436.08
   511.1 2436.96  544.74  2436.4  550.33 2436.41   674.6  2437.7   736.7 2440.23
#Mann= 9 ,-1 , 0
       0     .06       0   47.55     .12       0  173.46     .06       0
  363.98     .12       0   367.2    .045       0   390.1     .12       0
  395.62     .06       0  544.74     .07       0  550.33     .06       0
#XS Ineff= 2 , 0
                          558.89         2467.45
Permanent Ineff=
       F       F
Bank Sta=367.2,390.1
XS Rating Curve= 0 ,0
Exp/Cntr=0.3,0.1

Type RM Length L Ch R = 1 ,19154.1 ,308.3,383.1,309.8
XS GIS Cut Line= 3
     2153654.996      205669.603     2153487.024       205991.85
     2153293.295      206358.271
#Sta/Elev= 30
       0 2540.18    32.7 2532.89    52.4  2529.3    85.1 2522.23    91.7 2520.34
  117.372511.198   121.1 2509.08   127.7 2504.16   137.5 2498.74   147.3 2494.79
   173.5 2481.87   193.2 2473.07   222.6 2461.65   243.62455.445   284.8  2445.3
   304.5 2441.49   317.6 2439.58  336.88 2435.63   343.8 2434.32   353.6 2433.09
   363.7 2434.86  376.712434.554   422.1 2433.31   480.9 2433.48   510.3 2432.08
   565.7  2433.7   644.1 2434.53     693 2435.65     742 2438.95   777.9 2442.85
#Mann= 7 ,-1 , 0
       0     .06       0  117.37     .12       0   243.6     .06       0
  336.88     .12       0   343.8    .045       0   363.7     .12       0
  376.71     .06       0
Bank Sta=343.8,363.7
XS Rating Curve= 0 ,0
Exp/Cntr=0.3,0.1

Type RM Length L Ch R = 1 ,18771   ,293.1,313.5,302.3
XS GIS Cut Line= 2
     2153397.462      205542.299      2153058.92       206247.16
#Sta/Elev= 30
       0 2538.89    62.2 2528.43    85.1 2523.05    98.2 2519.21   130.9 2508.84
   170.1 2494.73   199.6 2485.02   202.8 2483.65   209.4 2479.13  283.982451.219
  284.972450.868   314.1 2440.47   323.9 2437.94     337 2433.38   340.3 2432.48
  349.712431.872   353.4 2431.91   369.7 2429.98     373 2430.02   379.5 2431.95
  391.212432.273   467.9 2431.68   484.2 2430.91   520.2 2431.41   526.8 2432.68
  549.162432.717   631.4 2432.57   683.8 2433.68     759 2440.62     782 2443.65
#Mann= 8 ,-1 , 0
       0     .06       0  283.98     .12       0  284.97     .06       0
  349.71     .12       0   353.4    .045       0   379.5     .12       0
  391.21     .06       0  549.16     .08       0
Bank Sta=353.4,379.5
XS Rating Curve= 0 ,0
Exp/Cntr=0.3,0.1

Type RM Length L Ch R = 1 ,18457.5 ,276.5,315.5,282.9
XS GIS Cut Line= 3
      2153086.01      205406.317     2152999.361      205771.501
     2152900.934      206160.355
#Sta/Elev= 30
       0  2508.9    35.9 2506.72    45.7  2505.6    58.8 2503.43    94.6 2495.66
   107.7  2492.2   114.2  2489.4   146.9 2479.02   166.4  2472.3   192.6 2465.05
   221.9 2457.84   264.4  2448.5   287.2 2442.96   329.6 2434.21  349.012431.452
   355.7 2430.25   362.3 2430.21   378.6    2428   381.8 2428.03   388.4 2430.94
   407.9 2429.75   424.2 2430.17   437.3 2429.65   447.1  2430.1   499.2 2430.57
   538.4 2431.58   551.4 2432.34  583.04 2432.52   701.4  2434.7   776.4 2437.89
#Mann= 5 ,-1 , 0
       0     .06       0  349.01     .12       0   362.3    .045       0
   388.4     .06       0  583.04     .08       0
Bank Sta=362.3,388.4
XS Rating Curve= 0 ,0
Exp/Cntr=0.3,0.1

Type RM Length L Ch R = 1 ,18142   ,301.4,309.6,295
XS GIS Cut Line= 2
     2152812.392      205417.299     2152699.051      206128.766
#Sta/Elev= 30
       0 2474.42    75.3 2460.83   108.1 2455.74     167  2444.6   199.8 2439.34
   232.5 2434.88   255.4 2430.57   265.2 2429.68   275.1 2427.84  285.242427.438
   291.4 2427.55   294.7 2427.46   301.3 2426.32   311.1 2427.77  315.152427.855
   320.9  2427.8   337.3 2428.56   347.1 2428.14   356.9 2429.14   366.8 2428.76
   389.7 2428.95   402.8 2428.24   412.6 2428.82   461.7 2429.64   484.7 2430.74
  499.972430.777   556.7 2431.33   628.8 2433.35   661.5 2435.28   720.4    2438
#Mann= 6 ,-1 , 0
       0     .06       0  285.24     .12       0   291.4    .045       0
   311.1     .12       0  315.15     .06       0  499.97     .08       0
Bank Sta=291.4,311.1
XS Rating Curve= 0 ,0
Exp/Cntr=0.3,0.1

Type RM Length L Ch R = 1 ,17832.4 ,218.4,218.9,228.2
XS GIS Cut Line= 2
     2152470.378      205424.243     2152576.281      206134.313
#Sta/Elev= 30
       0 2451.01    65.6 2444.69   108.2 2441.75   127.8 2439.45   147.5 2439.27
     177 2437.87     259 2430.61   331.1 2427.05   344.2 2427.05     354 2427.85
   363.9 2426.84     377 2426.45   399.9 2426.93   406.5 2426.52     413 2424.19
   416.3 2424.18   422.7 2426.55   426.2 2427.26   442.6 2427.18   452.4  2428.1
   468.8 2428.04   491.7 2429.41   501.6 2430.72   511.4 2430.06   524.5 2430.34
   573.82432.715   599.9 2433.52   652.4 2436.21   678.6 2436.76   717.9 2438.91
#Mann= 4 ,-1 , 0
       0     .06       0   399.9    .045       0   426.2     .06       0
   573.8     .08       0
Bank Sta=399.9,426.2
XS Rating Curve= 0 ,0
Exp/Cntr=0.3,0.1

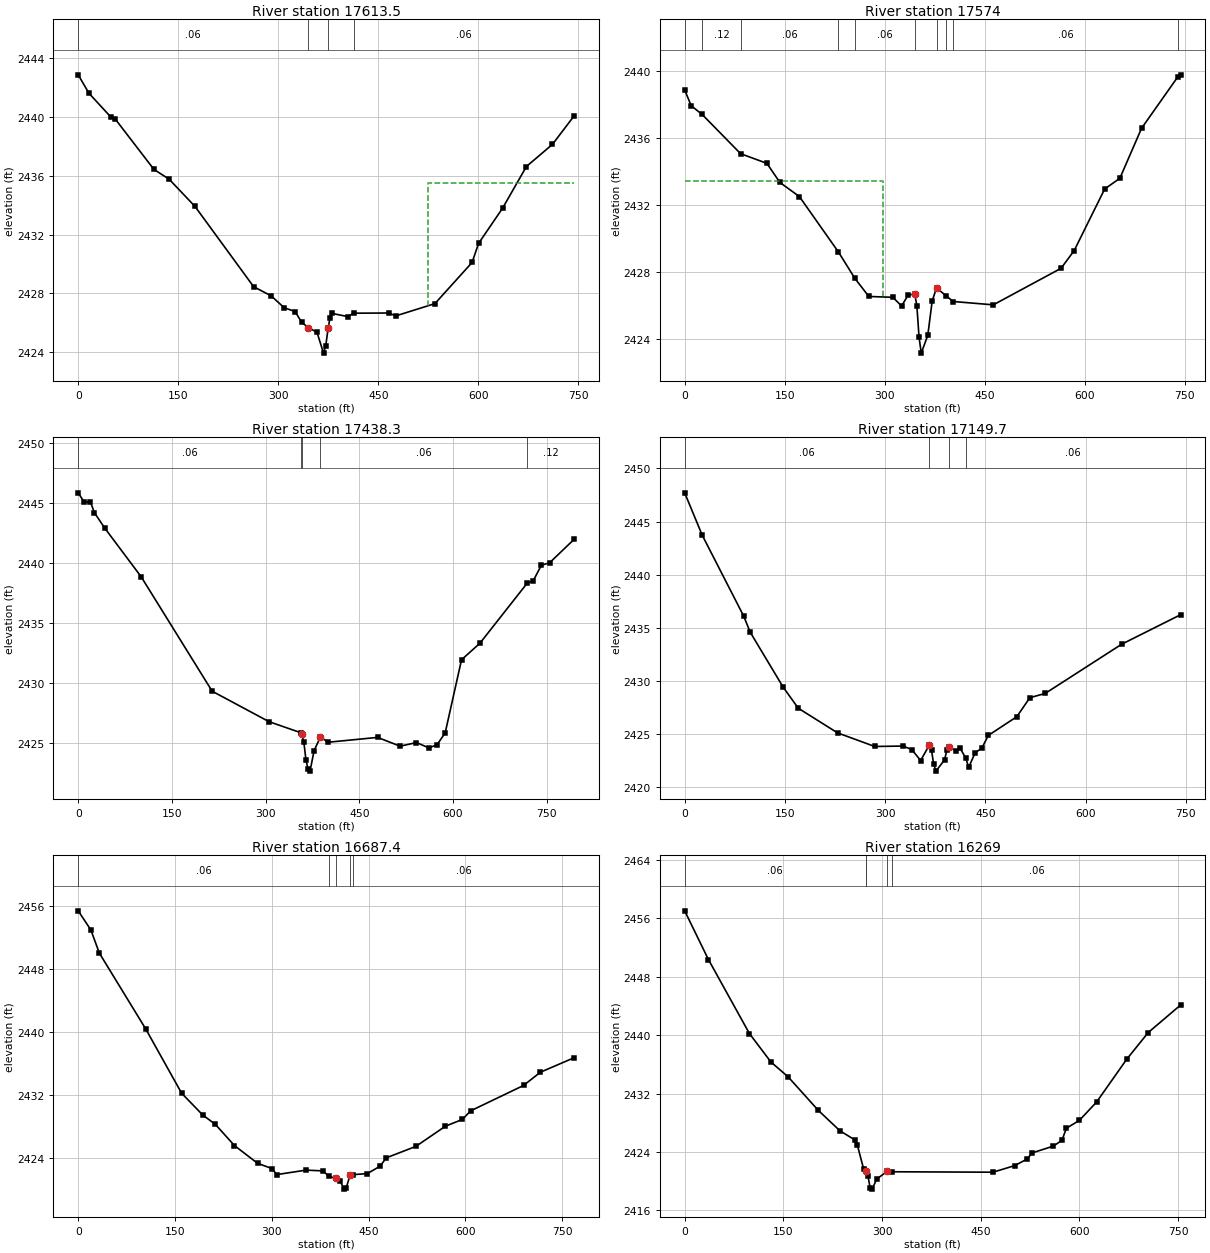
Type RM Length L Ch R = 1 ,17613.5 ,39.2,39.5,39.2
XS GIS Cut Line= 4
      2152402.67      205420.771     2152369.684      205658.618
     2152328.017      206023.202      2152308.92      206158.618
#Sta/Elev= 30
       0 2442.88    16.2 2441.62    48.7 2440.02    55.2 2439.89   113.6 2436.44
   136.3 2435.78   175.2 2433.92   263.1 2428.46   289.3 2427.84   308.9 2427.03
   325.3 2426.77   335.1 2426.04     345 2425.68   358.1 2425.36   367.9 2423.94
   371.2 2424.43     375 2425.68   377.7 2426.36     381 2426.64   403.9 2426.43
  413.312426.658   466.2 2426.67     476 2426.47     535 2427.31   590.7 2430.11
   600.5 2431.41   636.4  2433.8   672.2 2436.64   711.3 2438.15   743.8 2440.09
#Mann= 4 ,-1 , 0
       0     .06       0     345    .045       0     375     .12       0
  413.31     .06       0
#XS Ineff= 2 , 0
                          524.59          2435.5
Permanent Ineff=
       F       F
Bank Sta=345,375
XS Rating Curve= 0 ,0
Exp/Cntr=0.3,0.1

Type RM Length L Ch R = 1 ,17574   ,128.4,135.7,134.9
XS GIS Cut Line= 4
     2152364.475      205415.563     2152331.489       205653.41
     2152289.823      206017.993     2152270.725       206153.41
#Sta/Elev= 30
       0 2438.86     9.7 2437.92   26.242437.395   83.842435.057   123.3 2434.48
   142.8 2433.34     172  2432.5  230.582429.193  255.242427.619   276.2 2426.54
   312.2 2426.49   325.3 2425.97   335.1 2426.62     345 2426.69   348.2    2426
   351.5 2424.11   354.8 2423.16   364.6 2424.22   371.2 2426.27   377.7 2427.05
  391.932426.582   402.82426.239   462.9 2426.04   564.5 2428.22   584.2 2429.28
   629.9 2432.95   652.7 2433.59   685.2 2436.57  739.142439.613   743.8 2439.76
#Mann= 10 ,-1 , 0
       0     .06       0   26.24     .12       0   83.84     .06       0
  230.58     .12       0  255.24     .06       0     345    .045       0
   377.7     .06       0  391.93     .12       0   402.8     .06       0
  739.14    .016       0
#XS Ineff= 2 , 0
           297.6 2433.41
Permanent Ineff=
       F       F
Bank Sta=345,377.7
XS Rating Curve= 0 ,0
Exp/Cntr=0.3,0.1

Type RM Length L Ch R = 1 ,17438.3 ,300.2,288.5,283
XS GIS Cut Line= 3
     2152218.661      205383.702     2152209.962       205675.98
     2152128.364      206170.771
#Sta/Elev= 30
       0 2445.81     9.8 2445.01    19.5 2445.06      26 2444.15    42.2 2442.89
   100.7 2438.82   214.4 2429.28   305.5 2426.74  356.172425.823     358 2425.69
   361.2 2425.03   364.5 2423.58   367.8 2422.81   371.1 2422.62   377.6 2424.33
   387.5 2425.44   400.6 2425.03   479.2 2425.43   515.3  2424.7   541.5    2425
   561.2 2424.56   574.3 2424.81   587.4  2425.8   613.6  2431.9   643.1 2433.28
  719.092438.305   728.3 2438.47   741.4 2439.78   754.6 2439.98   793.9 2441.94
#Mann= 5 ,-1 , 0
       0     .06       0  356.17     .12       0     358    .045       0
   387.5     .06       0  719.09     .12       0
Bank Sta=358,387.5
XS Rating Curve= 0 ,0
Exp/Cntr=0.3,0.1

Type RM Length L Ch R = 1 ,17149.7 ,332.6,462.3,333.3
XS GIS Cut Line= 3
     2151921.161       205411.89     2151931.076       205784.45
     2151925.567      206153.944
#Sta/Elev= 30
       0 2447.71    26.2 2443.73    88.3 2436.11    98.1 2434.59   147.1 2429.45
     170 2427.44   228.8 2425.12   284.4 2423.84   326.9 2423.88     340 2423.54
   353.1 2422.52   366.2 2423.98   369.4 2423.48   372.5 2422.23     376 2421.52
     389 2422.59   392.3 2423.49   395.6 2423.77   405.4 2423.44   411.9 2423.71
  420.862422.721     425 2421.87   434.8 2423.26   444.6 2423.67   454.4 2424.88
     497 2426.64   516.6 2428.43   539.5 2428.83   653.9 2433.46   742.2 2436.24
#Mann= 4 ,-1 , 0
       0     .06       0   366.2    .045       0   395.6     .12       0
  420.86     .06       0
Bank Sta=366.2,395.6
XS Rating Curve= 0 ,0
Exp/Cntr=0.3,0.1

Type RM Length L Ch R = 1 ,16687.4 ,330,418.4,383.4
XS GIS Cut Line= 2
     2151676.975      205386.049     2151641.247      206154.066
#Sta/Elev= 30
       0 2455.39    19.6 2452.97    32.7 2450.04   104.7 2440.41   160.3 2432.27
     193 2429.51   212.7 2428.31   242.1 2425.64   278.1 2423.38     301  2422.7
   307.5 2421.95   353.3 2422.52   379.5 2422.42  388.712421.717   399.2 2421.49
   405.7 2421.18   412.2 2420.11   415.5 2420.29   421.7 2421.95   426.22421.945
   448.2 2422.08   467.8 2423.01   477.7 2424.08   523.5 2425.53   569.3 2428.09
   595.4 2428.94   608.5 2430.04   690.3 2433.25   716.5 2434.93   768.8 2436.77
#Mann= 5 ,-1 , 0
       0     .06       0  388.71     .12       0   399.2    .045       0
   421.7     .12       0   426.2     .06       0
Bank Sta=399.2,421.7
XS Rating Curve= 0 ,0
Exp/Cntr=0.3,0.1

Type RM Length L Ch R = 1 ,16269   ,315.1,345.2,338.9
XS GIS Cut Line= 2
     2151470.378      205356.535     2151364.475      206103.063
#Sta/Elev= 30
       0 2457.05    36.1 2450.37    98.4 2440.23   131.1 2436.33   157.4 2434.28
   203.2 2429.69     236  2426.9     259 2425.63   262.3    2425   272.1 2421.66
  275.232421.375   275.4 2421.36   278.6 2420.69   281.9 2419.12   285.2  2418.9
   291.8 2420.27   308.2 2421.36  315.922421.279   468.8 2421.22   501.6 2422.12
   521.2 2423.05   527.8 2423.85   560.6  2424.8   573.7  2425.6   580.2 2427.24
   599.9 2428.31   626.2 2430.83     672  2436.7   704.8 2440.37     754 2444.14
#Mann= 5 ,-1 , 0
       0     .06       0  275.23     .12       0   275.4    .045       0
   308.2     .12       0  315.92     .06       0
Bank Sta=275.4,308.2
XS Rating Curve= 0 ,0
Exp/Cntr=0.3,0.1

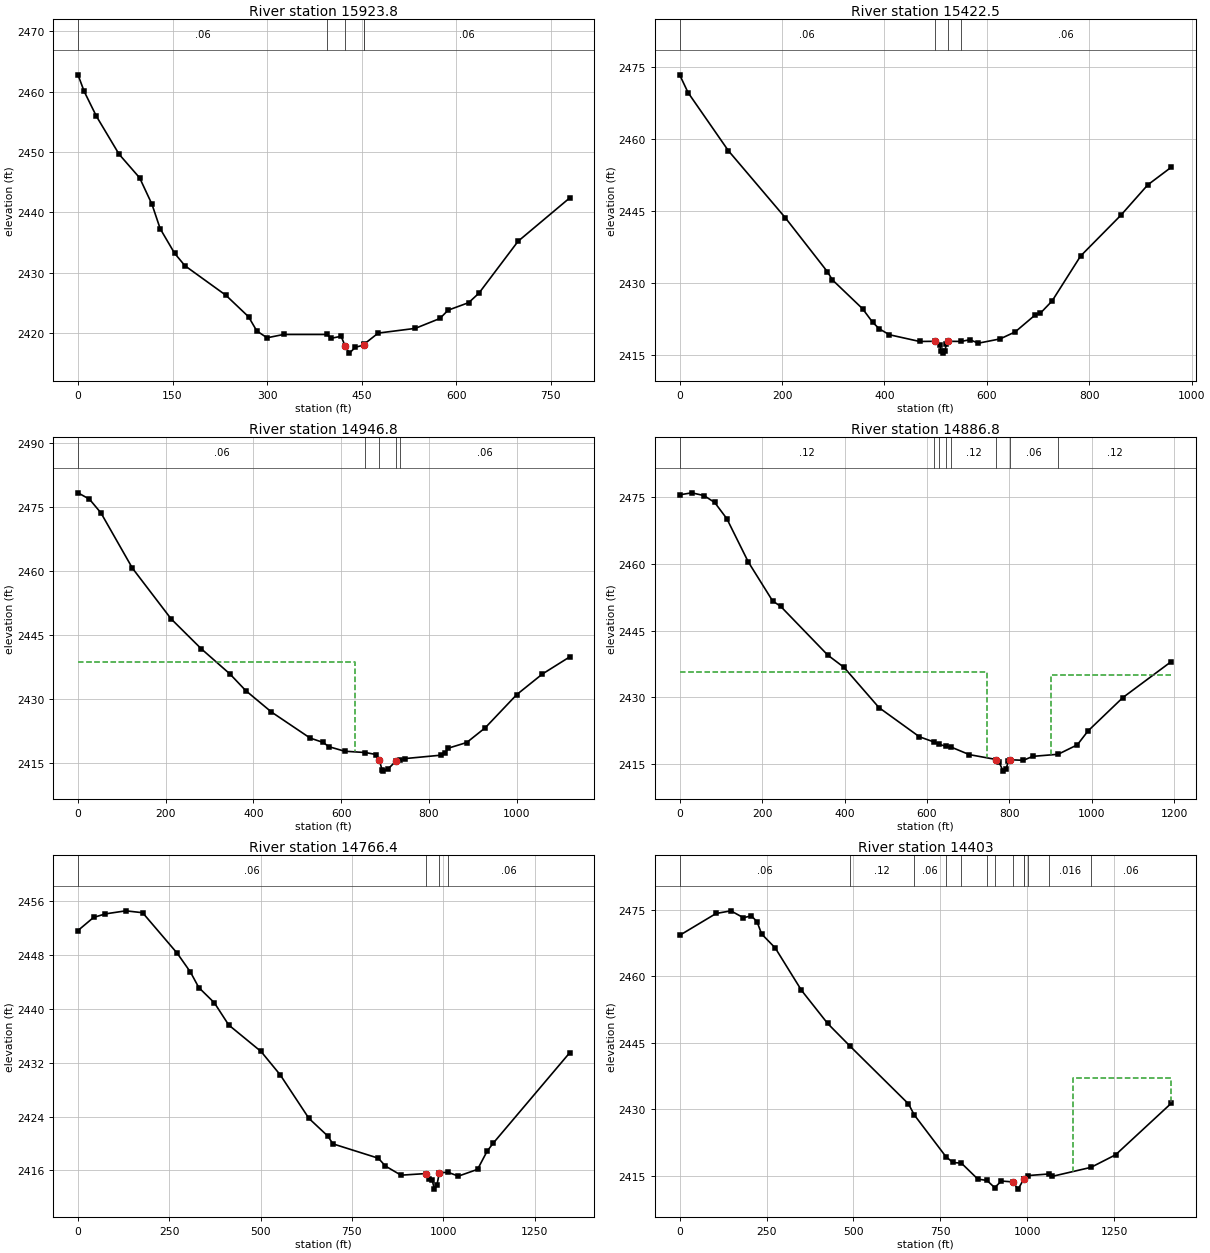
Type RM Length L Ch R = 1 ,15923.8 ,302.2,501.3,332.6
XS GIS Cut Line= 3
     2151232.864      205301.529     2151187.392      205601.327
     2151156.142      206077.021
#Sta/Elev= 30
       0 2462.81     9.8 2460.06    29.3 2455.93    65.2 2449.65    97.8 2445.74
   117.4 2441.35   130.4 2437.31   153.2 2433.25   169.6 2431.18   234.8 2426.27
   270.6 2422.72   283.7 2420.37     300 2419.23   326.1 2419.78  395.262419.782
   401.2 2419.14   417.5 2419.48     424 2417.85   430.6 2416.69   440.3 2417.67
   453.4 2418.02   454.62418.224   476.3 2420.01   535.1 2420.79   574.2 2422.43
   587.3 2423.81     620 2425.06   636.3 2426.64   698.3 2435.23     780 2442.39
#Mann= 5 ,-1 , 0
       0     .06       0  395.26     .12       0     424    .045       0
   453.4     .12       0   454.6     .06       0
Bank Sta=424,453.4
XS Rating Curve= 0 ,0
Exp/Cntr=0.3,0.1

Type RM Length L Ch R = 1 ,15422.5 ,315.3,475.8,293.7
XS GIS Cut Line= 2
     2150924.704      205127.918     2150909.831      206087.872
#Sta/Elev= 30
       0 2473.32    16.4 2469.62      95 2457.53   206.4 2443.54   288.4 2432.33
   298.2 2430.62   357.2  2424.6   376.8 2421.79   389.9 2420.41   409.6 2419.18
   468.6 2417.78   498.1 2417.81   507.9 2417.08   511.2 2415.84   514.4 2415.35
   517.7 2415.72     521 2417.16   524.3 2417.81  549.682417.785   566.9 2418.14
   583.2 2417.42   625.8 2418.31   655.3 2419.77   694.7 2423.33   704.5 2423.67
   727.4 2426.21   783.1 2435.58   861.8 2444.08   914.2 2450.39   960.1 2454.07
#Mann= 4 ,-1 , 0
       0     .06       0   498.1    .045       0   524.3     .12       0
  549.68     .06       0
Bank Sta=498.1,524.3
XS Rating Curve= 0 ,0
Exp/Cntr=0.3,0.1

Type RM Length L Ch R = 1 ,14946.8 ,54.9,60,56.8
XS GIS Cut Line= 4
     2150816.197      205008.561     2150713.434       205550.98
     2150649.198       205872.16     2150611.003      206110.007
#Sta/Elev= 30
       0 2478.37    26.1 2476.88    52.3 2473.66   124.1 2460.69   212.3  2448.8
   280.9  2441.8   346.3 2435.89   382.2    2432     441 2426.96   529.2 2420.85
   558.6 2419.84   571.7 2418.84   607.8 2417.77  655.092417.459   679.8 2416.99
   686.4 2415.82   692.9 2413.48   696.2  2413.1     706 2413.53   725.7 2415.56
  732.932415.604   745.3 2416.04   827.2 2416.84     837 2417.39   843.6 2418.47
   886.1 2419.81   928.4 2423.28  1000.1 2431.05  1058.6 2435.88  1120.5 2439.87
#Mann= 5 ,-1 , 0
       0     .06       0  655.09     .12       0   686.4    .045       0
   725.7     .12       0  732.93     .06       0
#XS Ineff= 2 , 0
          632.53 2438.75
Permanent Ineff=
       F       F
Bank Sta=686.4,725.7
XS Rating Curve= 0 ,0
Exp/Cntr=0.3,0.1

Type RM Length L Ch R = 1 ,14886.8 ,130,120.3,113.9
XS GIS Cut Line= 4
     2150785.815      204945.627     2150664.823      205557.924
     2150600.587      205879.105     2150562.392      206116.952
#Sta/Elev= 30
       0 2475.53    29.4 2475.98    58.8 2475.37      85 2473.81   114.4 2470.17
   166.6 2460.42   225.5 2451.68   245.1 2450.45   359.4 2439.49   398.7 2436.74
   483.6 2427.69   581.7 2421.13   616.42419.982  629.87 2419.44  646.042418.982
  658.972418.798   702.8 2417.12   768.3 2416.02   774.8 2415.48   784.6 2413.41
   791.2 2413.78   797.7  2415.6   801.7 2415.97   833.8 2415.84   856.7 2416.73
  918.142417.197   964.7 2419.32   990.7 2422.44  1075.4 2429.96  1192.6 2438.03
#Mann= 8 ,-1 , 0
       0     .12       0   616.4     .06       0  629.87     .12       0
  646.04     .06       0  658.97     .12       0   768.3    .045       0
   801.7     .06       0  918.14     .12       0
#XS Ineff= 2 , 0
          744.51 2435.71  901.89            2435
Permanent Ineff=
       F       F
Bank Sta=768.3,801.7
XS Rating Curve= 0 ,0
Exp/Cntr=0.3,0.1

Type RM Length L Ch R = 1 ,14766.4 ,260.7,363.4,196.7
XS GIS Cut Line= 3
     2150619.221      204785.832     2150529.623      205596.552
     2150501.845      206126.066
#Sta/Elev= 30
       0  2451.6    42.6 2453.54    75.3 2454.07     131 2454.52   176.9 2454.24
   271.9 2448.21   307.9 2445.43   330.8 2443.13   373.4 2440.87   412.7 2437.58
   501.2 2433.65   553.6 2430.19   632.2 2423.73   684.6 2421.07   697.7 2419.95
   822.2 2417.82   841.8 2416.65   884.4  2415.3   953.1 2415.54   959.7 2414.66
   969.5 2414.58     976 2413.23   982.6 2413.78   989.4 2415.69 1013.91 2415.71
  1041.5 2415.16  1093.9 2416.16    1120 2418.84  1136.4 2420.02  1345.9 2433.44
#Mann= 4 ,-1 , 0
       0     .06       0   953.1    .045       0   989.4     .12       0
 1013.91     .06       0
Bank Sta=953.1,989.4
XS Rating Curve= 0 ,0
Exp/Cntr=0.3,0.1

Type RM Length L Ch R = 1 ,14403   ,42.3,71.1,96.5
XS GIS Cut Line= 4
     2149631.808      205113.523     2150302.192      205572.247
     2150347.331      205787.525     2150461.915      206152.108
#Sta/Elev= 30
       0 2469.28   104.8 2474.21   147.4 2474.81   183.4 2473.25   206.4 2473.68
   222.7 2472.34   235.8 2469.59   275.1 2466.42   350.5 2456.87   425.8 2449.39
  488.912444.375   658.4 2431.24  675.042428.758  765.912419.358   786.1 2418.02
  810.742417.869   857.6 2414.29  884.292413.958  906.49 2412.34   925.5 2413.84
   957.9 2413.64     974 2412.01   990.2 2414.29  990.532414.339 1001.932415.069
 1063.072415.433  1071.5 2414.88 1183.572416.925  1254.4 2419.76  1414.4 2431.38
#Mann= 13 ,-1 , 0
       0     .06       0  488.91     .12       0  675.04     .06       0
  765.91    .016       0  810.74     .06       0  884.29     .12       0
  906.49     .06       0   957.9    .045       0   990.2    .016       0
  990.53     .12       0 1001.93     .06       0 1063.07    .016       0
 1183.57     .06       0
#XS Ineff= 2 , 0
                          1131.9         2437.14
Permanent Ineff=
       F       F
Bank Sta=957.9,990.2
XS Rating Curve= 0 ,0
Exp/Cntr=0.3,0.1

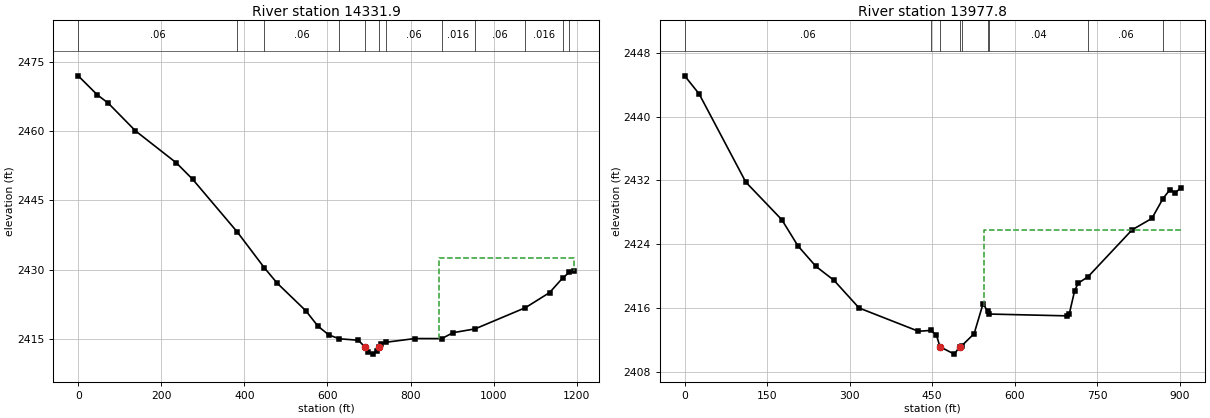
Type RM Length L Ch R = 1 ,14331.9 ,381.4,354.2,343.5
XS GIS Cut Line= 4
     2149709.933      205402.151     2150263.998      205586.136
     2150309.137      205801.414     2150421.738      206174.721
#Sta/Elev= 30
       0 2472.03    45.9 2467.91    72.2 2466.11   137.8 2460.09   236.2 2453.15
   275.5 2449.58  382.952438.142  448.172430.363   478.9 2427.05   547.7 2421.07
   577.2  2417.7   603.2 2415.82  628.152414.982   674.4 2414.66   690.6 2413.14
     697 2412.11     710 2411.65   719.7 2412.39   722.9 2413.12   729.4  2413.9
   740.72414.225   810.3 2415.03  875.072415.017   902.1  2416.3  955.182417.125
 1076.482421.729  1134.7 2425.01 1165.822428.147 1181.832429.386  1193.7 2429.76
#Mann= 12 ,-1 , 0
       0     .06       0  382.95     .12       0  448.17     .06       0
  628.15    .016       0   690.6    .045       0   722.9    .016       0
   740.7     .06       0  875.07    .016       0  955.18     .06       0
 1076.48    .016       0 1165.82     .08       0 1181.83    .016       0
#XS Ineff= 2 , 0
                           868.6         2432.41
Permanent Ineff=
       F       F
Bank Sta=690.6,722.9
XS Rating Curve= 0 ,0
Exp/Cntr=0.3,0.1

Type RM Length L Ch R = 1 ,13977.8 ,243.2,249.2,252.5
XS GIS Cut Line= 3
     2149668.266      205693.818     2150053.019      205941.853
     2150420.701      206191.176
#Sta/Elev= 30
       0 2445.13    26.2 2442.87   111.2 2431.79   176.6 2427.08     206 2423.79
   238.7 2421.22   271.4 2419.48   317.2    2416   425.1 2413.08  447.642413.184
   457.8 2412.62   464.3 2411.13   490.4 2410.21   500.2 2411.14  503.842411.256
   526.4 2412.77   542.7 2416.54   550.92415.595  553.172415.241   696.2 2415.01
   699.5 2415.26   709.3 2418.18   715.8 2419.12  733.63 2419.92   813.8 2425.81
   849.8 2427.24  869.952429.731   882.4 2430.83   892.2 2430.46     902 2431.04
#Mann= 9 ,-1 , 0
       0     .06       0  447.64     .12       0   464.3    .045       0
   500.2     .12       0  503.84     .06       0   550.9     .12       0
  553.17     .04       0  733.63     .06       0  869.95    .016       0
#XS Ineff= 2 , 0
                          544.77         2425.82
Permanent Ineff=
       F       F
Bank Sta=464.3,500.2
XS Rating Curve= 0 ,0
Exp/Cntr=0.3,0.1