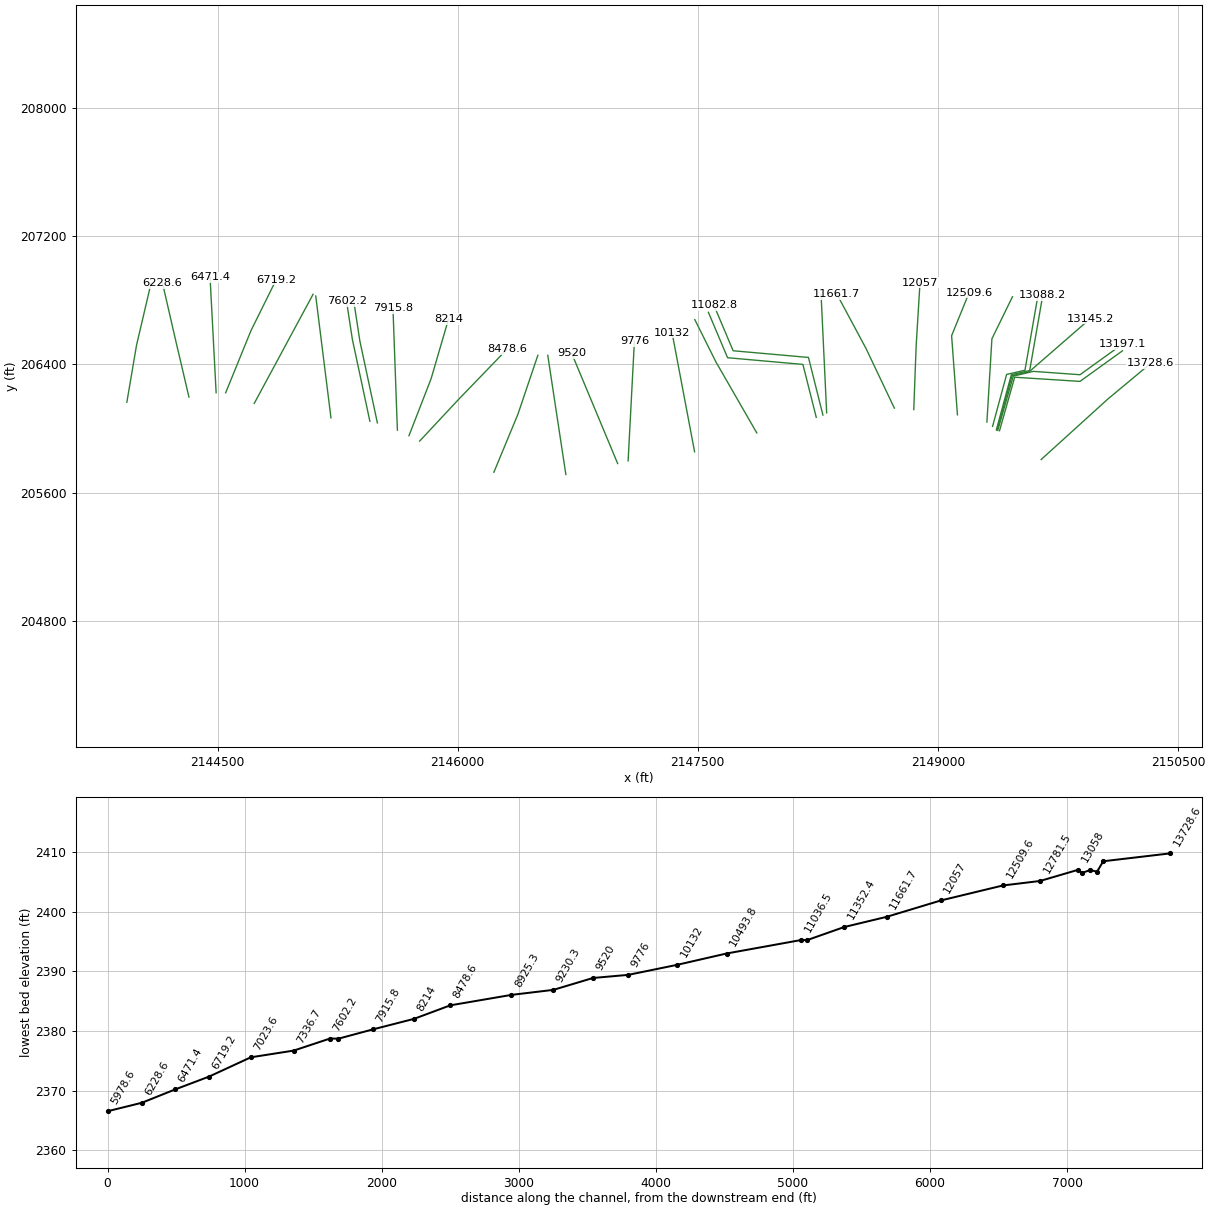
HEC-RAS study KITCHENCK.prj: KITCHENCK

--- KITCHENCK.g01 (geometry) --- (continued)

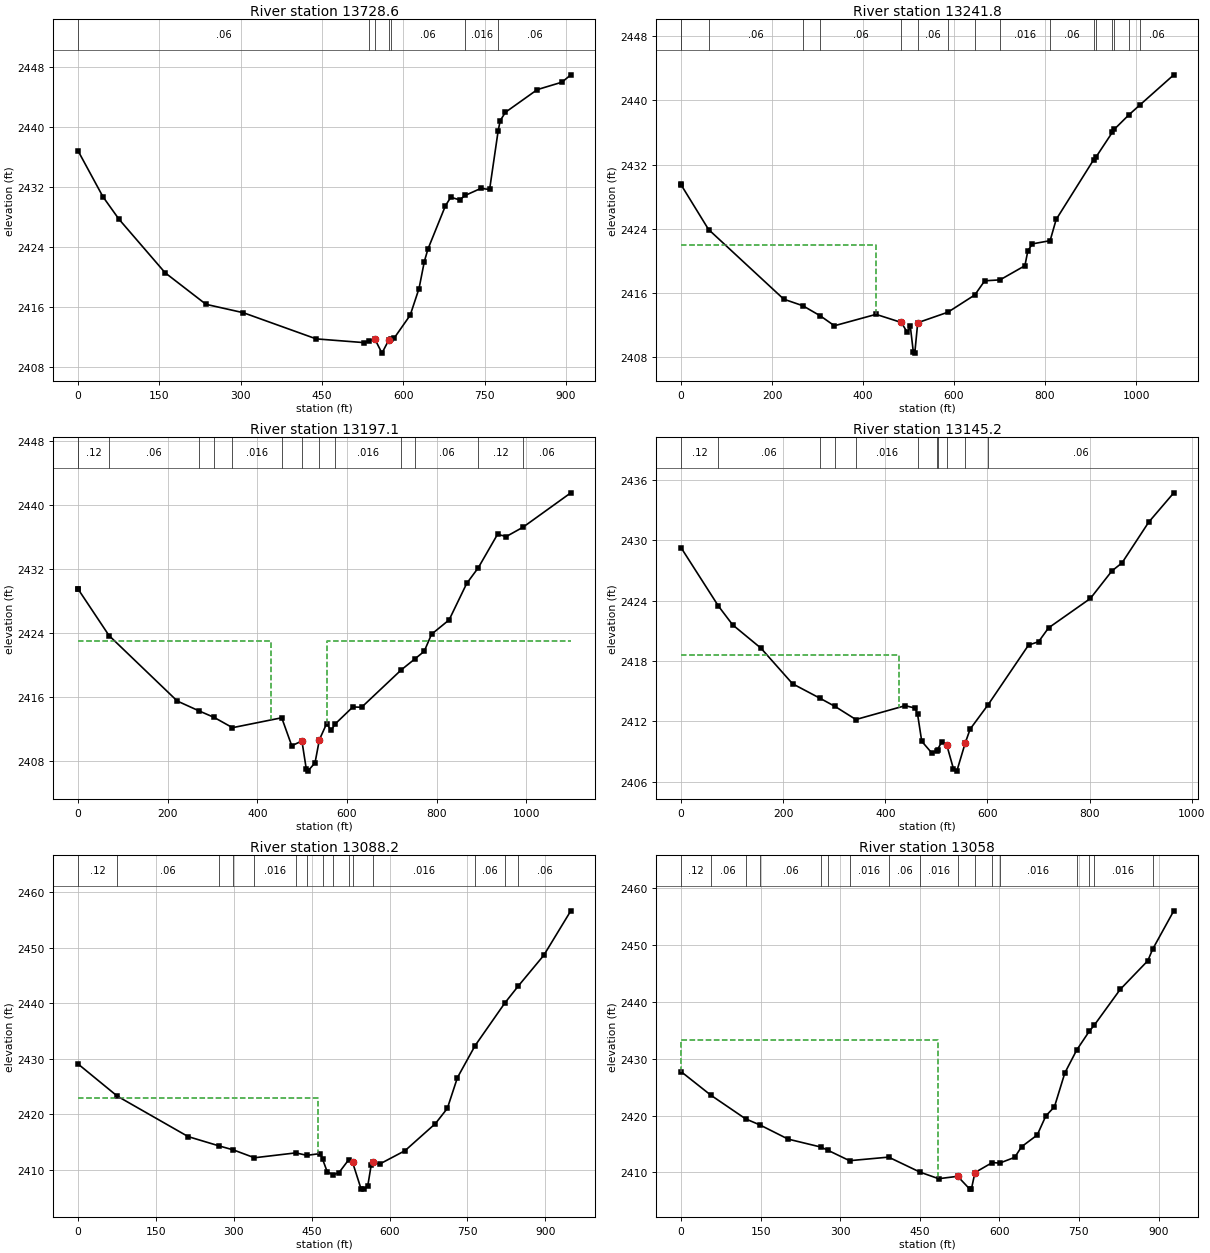
Type RM Length L Ch R = 1 ,13728.6 ,511.4,486.7,272.2
XS GIS Cut Line= 3
     2149644.828      205805.797     2150060.433      206182.028
     2150328.444      206404.646
#Sta/Elev= 30
       0 2436.82    45.9  2430.7    75.4 2427.71   160.6 2420.56     236 2416.35
   304.9 2415.23   439.3 2411.74   527.8 2411.24  537.562411.518   547.5 2411.72
   560.6 2409.84   573.6 2411.64  576.792411.737   583.4 2411.87   612.7  2414.9
     629 2418.46   638.8 2422.06   645.3 2423.69   677.8 2429.51   687.6 2430.63
   703.9 2430.28   714.72430.893     743 2431.81   759.2 2431.67  775.042439.524
   778.8 2440.86   788.5 2441.97   847.2 2444.99   892.7 2445.98     909 2446.96
#Mann= 7 ,-1 , 0
       0     .06       0  537.56     .12       0   547.5    .045       0
   573.6     .12       0  576.79     .06       0   714.7    .016       0
  775.04     .06       0
Bank Sta=547.5,573.6
XS Rating Curve= 0 ,0
Exp/Cntr=0.3,0.1

Type RM Length L Ch R = 1 ,13241.8 ,48.4,44.8,202.9
XS GIS Cut Line= 4
     2149384.614      205985.051     2149479.276      206318.775
     2149887.262      206292.733     2150152.887      206483.705
#Sta/Elev= 30
       0 2429.58    1.042429.407   60.532423.921   225.8 2415.24  267.732414.424
  306.162413.161   337.1 2411.93   428.6 2413.35   484.2 2412.34   497.3 2411.09
   503.9 2411.85   510.4 2408.72   513.7 2408.52   520.2 2412.31  586.522413.618
  645.722415.772   667.4 2417.53  701.032417.645   755.7 2419.41   762.2 2421.26
   772.1 2422.13  811.132422.529   824.4 2425.17  906.65  2432.6  911.542432.911
  947.922436.031  952.552436.425   984.32438.209    10092439.464  1082.9 2443.19
#Mann= 17 ,-1 , 0
       0     .06       0    1.04     .12       0   60.53     .06       0
  267.73     .12       0  306.16     .06       0   484.2    .045       0
   520.2     .06       0  586.52     .08       0  645.72     .12       0
  701.03    .016       0  811.13     .06       0  906.65     .12       0
  911.54     .06       0  947.92    .016       0  952.55     .12       0
   984.3    .016       0    1009     .06       0
#XS Ineff= 2 , 0
          428.25 2422.04
Permanent Ineff=
       F       F
Bank Sta=484.2,520.2
XS Rating Curve= 0 ,0
Exp/Cntr=0.3,0.1

Type RM Length L Ch R = 1 ,13197.1 ,16.4,51.9,81.6
XS GIS Cut Line= 5
     2149373.764      205987.655     2149470.595      206325.719
     2149595.595      206355.233     2149887.262        206334.4
     2150152.887      206525.372
#Sta/Elev= 30
       0 2429.55     .292429.501    69.12423.714   221.4 2415.53  270.182414.293
   303.72413.483  344.64  2412.2  454.552413.438   476.9 2409.94   499.6 2410.54
   509.3 2407.04   512.6 2406.77   528.8  2407.8   538.6  2410.7   554.8 2412.71
   564.6 2411.86  574.142412.683   613.3 2414.79   632.8 2414.75  721.692419.443
   751.32420.774   772.5 2421.74   788.9 2423.88   828.1 2425.67   867.4 2430.23
  893.312432.195   936.1 2436.36   955.7 2436.09  992.92 2437.25  1099.7 2441.55
#Mann= 14 ,-1 , 0
       0     .06       0     .29     .12       0    69.1     .06       0
  270.18     .12       0   303.7     .06       0  344.64    .016       0
  454.55     .12       0   499.6    .045       0   538.6     .12       0
  574.14    .016       0  721.69     .12       0   751.3     .06       0
  893.31     .12       0  992.92     .06       0
#XS Ineff= 2 , 0
          429.76 2423.06  555.11         2422.99
Permanent Ineff=
       F       F
Bank Sta=499.6,538.6
XS Rating Curve= 0 ,0
Exp/Cntr=0.3,0.1

Type RM Length L Ch R = 1 ,13145.2 ,35.2,57,82.4
XS GIS Cut Line= 4
     2149369.033      205988.914     2149462.783      206328.323
     2149569.554      206352.629     2149949.762       206682.49
#Sta/Elev= 30
       0 2429.28   73.312423.462   101.1  2421.6   156.5 2419.28   218.4 2415.74
  271.69 2414.31   301.62413.485  342.422412.182   439.1 2413.56   458.4 2413.32
  463.182412.735   471.4 2410.02     491 2408.86  500.432409.071  502.282409.197
   510.6 2409.95   520.5 2409.63   533.5 2407.28   540.1 2407.05   556.4 2409.82
   566.2 2411.23  601.652413.673   680.6 2419.59   700.2 2419.92   719.8  2421.3
   801.6 2424.22     844 2426.97   863.6 2427.76     916 2431.82     965 2434.73
#Mann= 11 ,-1 , 0
       0     .12       0   73.31     .06       0  271.69     .12       0
   301.6     .06       0  342.42    .016       0  463.18     .12       0
  500.43     .06       0  502.28     .12       0   520.5    .045       0
   556.4     .12       0  601.65     .06       0
#XS Ineff= 2 , 0
          426.23 2418.62
Permanent Ineff=
       F       F
Bank Sta=520.5,556.4
XS Rating Curve= 0 ,0
Exp/Cntr=0.3,0.1

Type RM Length L Ch R = 1 ,13088.2 ,30.4,30.2,30.3
XS GIS Cut Line= 4
     2149365.083      205991.127     2149458.442        206334.4
     2149573.026      206360.441     2149654.623      206829.191
#Sta/Elev= 30
       0 2429.07   75.762423.273   212.1    2416  271.692414.326  298.99 2413.61
  339.752412.193  419.442413.074  440.61 2412.63   466.7 2412.95  470.892411.938
   479.8 2409.69  491.132409.115   502.6 2409.53  521.112411.819   528.6  2411.4
   544.9 2406.63   551.5 2406.55     558 2407.15   564.5 2410.86   567.8 2411.41
   580.8 2411.06   629.7 2413.47   688.3 2418.35   711.2 2421.08   730.7 2426.63
  764.692432.374  822.162440.071  847.942443.112   896.9 2448.62     949 2456.63
#Mann= 15 ,-1 , 0
       0     .12       0   75.76     .06       0  271.69     .12       0
  298.99     .06       0  339.75    .016       0  419.44     .06       0
  440.61    .016       0  470.89     .12       0  491.13     .06       0
  521.11    .016       0   528.6    .045       0   567.8    .016       0
  764.69     .06       0  822.16     .12       0  847.94     .06       0
#XS Ineff= 2 , 0
           462.8 2422.96
Permanent Ineff=
       F       F
Bank Sta=528.6,567.8
XS Rating Curve= 0 ,0
Exp/Cntr=0.3,0.1

Type RM Length L Ch R = 1 ,13058   ,253,276.5,280.9
XS GIS Cut Line= 4
     2149341.212      206012.394     2149428.929      206336.136
     2149543.512      206362.177     2149625.109      206830.927
#Sta/Elev= 30
       0 2427.72   56.262423.573  121.692419.422  149.172418.331   201.9 2415.86
  263.262414.475  276.952413.898  317.632412.074  391.26  2412.7  450.542410.058
   485.5 2408.91   521.4 2409.33   544.2 2407.08   547.4 2407.16     554 2409.99
  586.832411.755  600.392411.646   628.9 2412.66   641.9 2414.53   671.3 2416.58
   687.6 2419.94   703.8 2421.54   723.4 2427.49  745.782431.512  769.472434.811
  778.532435.826   827.7 2442.15   879.8 2447.19  888.79  2449.2   928.7 2455.95
#Mann= 17 ,-1 , 0
       0     .12       0   56.26     .06       0  121.69     .12       0
  149.17     .06       0  263.26     .12       0  276.95     .06       0
  317.63    .016       0  391.26     .06       0  450.54    .016       0
   521.4    .045       0     554     .12       0  586.83     .06       0
  600.39    .016       0  745.78     .12       0  769.47     .06       0
  778.53    .016       0  888.79     .12       0
#XS Ineff= 2 , 0
          484.24 2433.29
Permanent Ineff=
       F       F
Bank Sta=521.4,554
XS Rating Curve= 0 ,0
Exp/Cntr=0.3,0.1

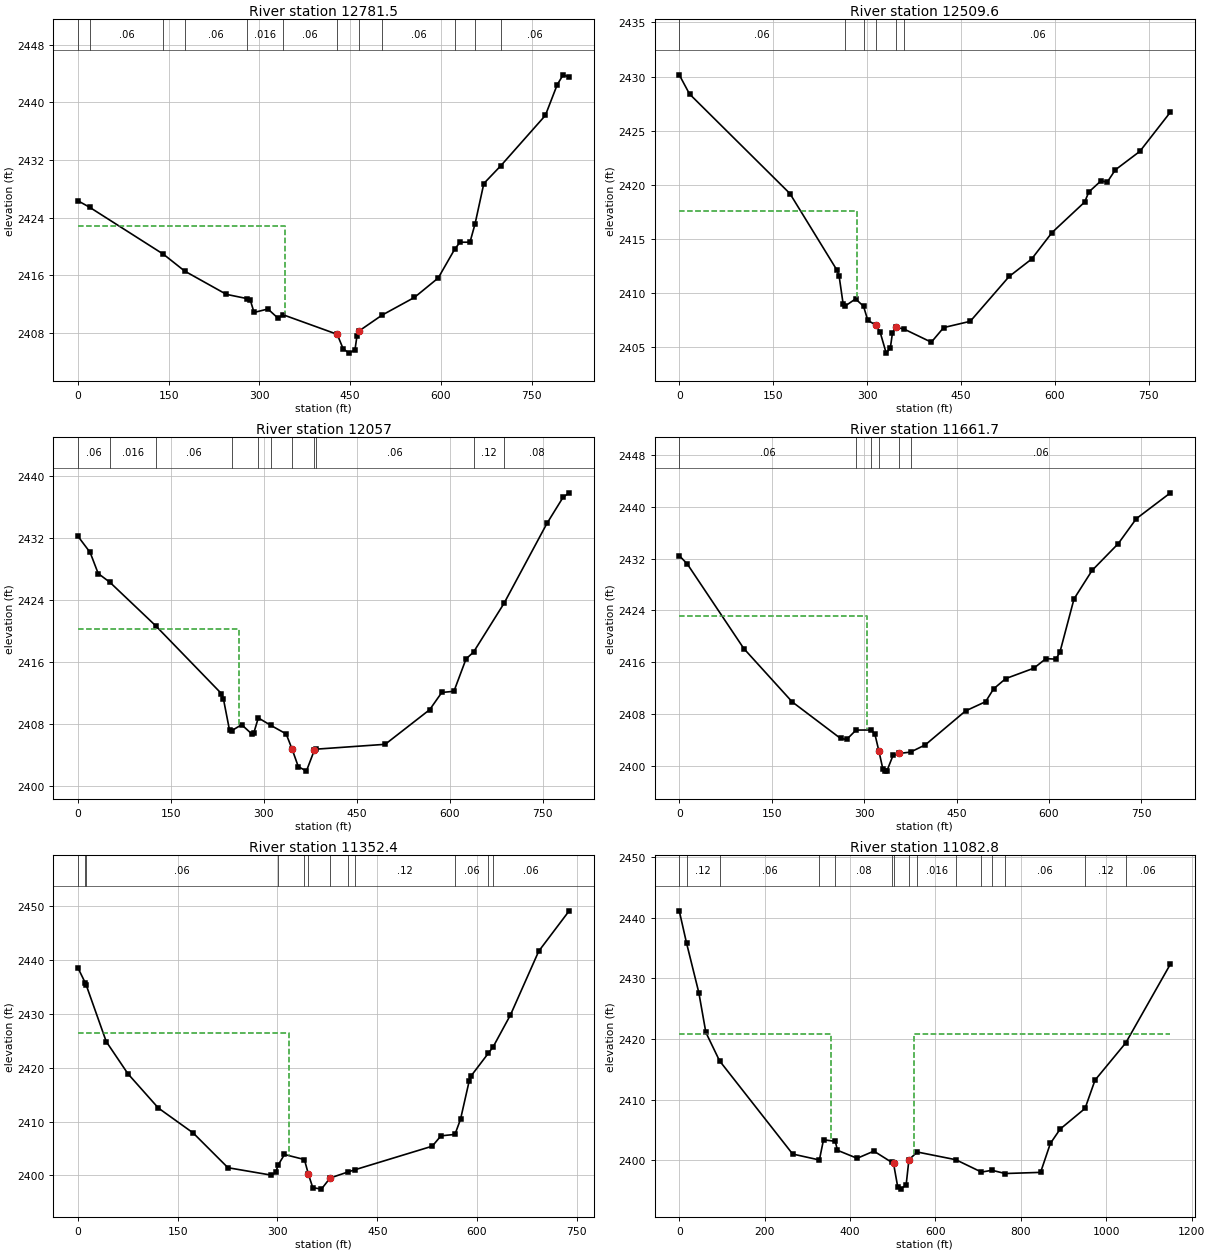
Type RM Length L Ch R = 1 ,12781.5 ,260.9,271.8,262.6
XS GIS Cut Line= 3
     2149305.838      206039.304     2149337.088      206558.401
     2149465.561      206820.554
#Sta/Elev= 30
       0 2426.33   19.162425.442  141.372418.915  176.422416.585   245.3 2413.36
  280.162412.759   284.6 2412.62   291.1 2410.85     314 2411.33   330.3 2410.08
  339.352410.521   428.5 2407.82   438.3 2405.82   448.1 2405.21   457.9 2405.68
   461.2 2407.59   464.4 2408.27  502.462410.469   556.1 2412.93   595.5 2415.63
  622.922419.647   631.6 2420.59     648 2420.59  656.382423.132   670.9 2428.73
  699.112431.207   772.6 2438.17   792.3 2442.45   802.1  2443.8     812 2443.48
#Mann= 12 ,-1 , 0
       0     .12       0   19.16     .06       0  141.37     .12       0
  176.42     .06       0  280.16    .016       0  339.35     .06       0
   428.5    .045       0   464.4     .12       0  502.46     .06       0
  622.92    .016       0  656.38     .12       0  699.11     .06       0
#XS Ineff= 2 , 0
          341.74 2422.77
Permanent Ineff=
       F       F
Bank Sta=428.5,464.4
XS Rating Curve= 0 ,0
Exp/Cntr=0.3,0.1

Type RM Length L Ch R = 1 ,12509.6 ,430.5,452.7,431.6
XS GIS Cut Line= 3
     2149121.811      206084.443     2149085.352      206577.499
     2149194.901      206846.322
#Sta/Elev= 30
       0 2430.16    16.4 2428.39   176.8 2419.19   252.1  2412.1   255.4 2411.56
   261.9 2408.96  264.762408.787   281.6 2409.46  294.372408.784   301.2 2407.48
   314.3 2407.03   320.9 2406.39   330.6 2404.45   337.2 2404.93   340.5 2406.27
   345.6 2406.85  359.532406.662   402.7 2405.46   422.4 2406.81   464.9 2407.39
     527 2411.53   562.9 2413.14   595.5 2415.59   647.7 2418.41   654.2 2419.33
   673.8 2420.37   683.6 2420.24   696.6 2421.38   735.8 2423.09   784.7 2426.72
#Mann= 6 ,-1 , 0
       0     .06       0  264.76    .016       0  294.37     .06       0
   314.3    .045       0   345.6     .12       0  359.53     .06       0
#XS Ineff= 2 , 0
          283.48 2417.54
Permanent Ineff=
       F       F
Bank Sta=314.3,345.6
XS Rating Curve= 0 ,0
Exp/Cntr=0.3,0.1

Type RM Length L Ch R = 1 ,12057   ,377.5,395.3,406.6
XS GIS Cut Line= 3
      2148848.94      206116.896     2148864.049      206517.572
     2148888.034      206908.169
#Sta/Elev= 30
       0 2432.23    19.6 2430.15    32.6 2427.43   51.482426.297  125.252420.694
   231.4 2411.93   234.7 2411.21   244.5 2407.18  248.342407.169     264 2407.92
   280.4 2406.72   283.6 2406.86  290.842408.797   310.82407.848   335.8 2406.73
   345.5 2404.74   355.3 2402.52   368.4 2401.93   381.4 2404.66  383.192404.758
   495.5 2405.39   567.3 2409.86   586.8 2412.08   606.4 2412.23     626 2416.42
  637.972417.282  687.062423.562   756.4 2433.89   782.5 2437.27   792.3 2437.84
#Mann= 11 ,-1 , 0
       0     .06       0   51.48    .016       0  125.25     .06       0
  248.34    .016       0  290.84     .12       0   310.8     .06       0
   345.5    .045       0   381.4     .12       0  383.19     .06       0
  637.97     .12       0  687.06     .08       0
#XS Ineff= 2 , 0
          260.28 2420.26
Permanent Ineff=
       F       F
Bank Sta=345.5,381.4
XS Rating Curve= 0 ,0
Exp/Cntr=0.3,0.1

Type RM Length L Ch R = 1 ,11661.7 ,323,309.2,294.5
XS GIS Cut Line= 3
     2148727.713       206126.11     2148550.475      206498.573
     2148368.233      206837.359
#Sta/Elev= 30
       0 2432.45    13.1 2431.15   104.8  2418.1   183.3 2409.87   261.9 2404.22
   271.7 2404.07  286.922405.514  311.632405.533   317.6 2404.86   324.1 2402.24
   330.6 2399.44   333.9 2399.18   337.2 2399.26     347 2401.62   356.8 2401.91
  375.342402.117   399.4 2403.24   464.6 2408.47   497.2  2409.9   510.3 2411.89
   529.8 2413.46   575.5 2415.07     595 2416.54   611.4 2416.47   617.9 2417.58
   640.7 2425.77     670 2430.16   712.4 2434.29   741.8 2438.15   797.2 2442.14
#Mann= 6 ,-1 , 0
       0     .06       0  286.92    .016       0  311.63     .08       0
   324.1    .045       0   356.8     .12       0  375.34     .06       0
#XS Ineff= 2 , 0
          304.67 2423.14
Permanent Ineff=
       F       F
Bank Sta=324.1,356.8
XS Rating Curve= 0 ,0
Exp/Cntr=0.3,0.1

Type RM Length L Ch R = 1 ,11352.4 ,95,269.6,325.6
XS GIS Cut Line= 2
     2148304.914      206096.935     2148270.006      206834.691
#Sta/Elev= 30
       0 2438.48   10.782435.746   12.142435.379    42.5 2424.82    75.2 2418.84
   120.9  2412.5   173.2 2407.88   225.5 2401.44   290.9 2400.06   297.4 2400.56
  300.862401.912   310.5 2403.89  340.462402.955   346.4 2400.27     353 2397.75
     366 2397.47   379.1 2399.53  406.082400.653  416.242401.056   532.7 2405.43
   545.8 2407.35  566.822407.613   575.2 2410.42   588.2  2417.5   591.5 2418.52
     6172422.653   624.2 2423.83   650.3 2429.76   692.8 2441.58   738.6 2449.06
#Mann= 12 ,-1 , 0
       0     .06       0   10.78     .12       0   12.14     .06       0
  300.86    .016       0  340.46     .12       0   346.4    .045       0
   379.1     .12       0  406.08     .06       0  416.24     .12       0
  566.82     .06       0     617     .12       0   624.2     .06       0
#XS Ineff= 2 , 0
          316.77 2426.35
Permanent Ineff=
       F       F
Bank Sta=346.4,379.1
XS Rating Curve= 0 ,0
Exp/Cntr=0.3,0.1

Type RM Length L Ch R = 1 ,11082.8 ,161.1,46.3,457.6
XS GIS Cut Line= 4
     2148281.533      206082.707     2148191.255      206442.082
     2147720.769      206483.749     2147600.977      206766.735
#Sta/Elev= 30
       0 2441.13   17.092435.819    45.9 2427.63    62.3  2421.1   94.432416.414
   265.6 2401.06  328.122400.083   337.8 2403.41  365.312403.157   370.5 2401.68
   416.5 2400.36   455.8 2401.54     4982399.674   501.7 2399.54   511.6 2395.64
   518.1 2395.28   531.3 2395.98   537.8 2400.12   557.32401.395  647.562400.127
  707.652398.088  732.292398.385  763.26 2397.85   846.1 2398.04     869 2402.81
   891.9 2405.17  950.252408.578   973.6 2413.24  1045.6 2419.38  1150.2 2432.37
#Mann= 15 ,-1 , 0
       0     .06       0   17.09     .12       0   94.43     .06       0
  328.12    .016       0  365.31     .08       0     498     .12       0
   501.7    .045       0   537.8     .08       0   557.3    .016       0
  647.56     .12       0  707.65     .06       0  732.29     .12       0
  763.26     .06       0  950.25     .12       0  1045.6     .06       0
#XS Ineff= 2 , 0
          355.61 2420.77  550.82         2420.84
Permanent Ineff=
       F       F
Bank Sta=501.7,537.8
XS Rating Curve= 0 ,0
Exp/Cntr=0.3,0.1

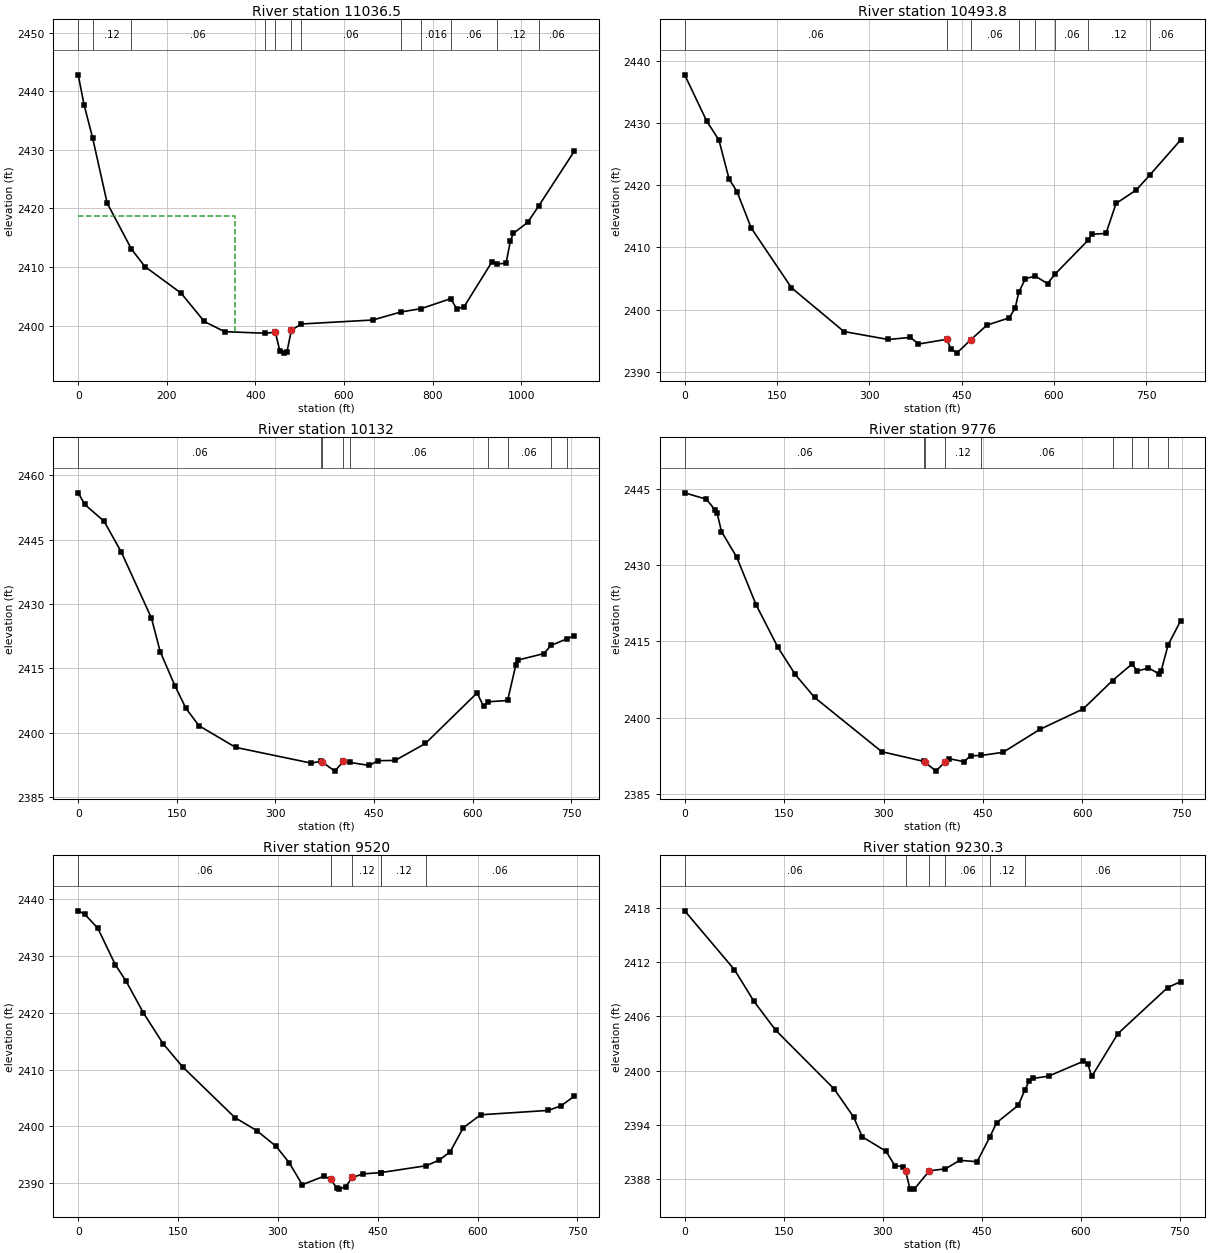
Type RM Length L Ch R = 1 ,11036.5 ,571.3,542.6,91.2
XS GIS Cut Line= 4
     2148239.866      206068.818     2148156.533      206398.679
     2147686.047      206440.346     2147566.255      206723.332
#Sta/Elev= 30
       0 2442.84    13.1 2437.76    32.52432.079    65.4 2420.91  120.282413.048
   150.5 2410.08   232.3 2405.53   284.6 2400.69   330.4 2398.95  421.732398.679
   445.2 2398.85     455 2395.72   464.9 2395.28   471.4 2395.54   481.3 2399.17
   503.5 2400.26     665 2400.94  729.352402.322  774.212402.882  840.952404.585
     855 2402.83   871.4 2403.22   933.5 2410.79  945.142410.467   966.2 2410.69
     976 2414.52   982.6 2415.75  1015.2 2417.65  1039.92420.449  1119.8 2429.75
#Mann= 12 ,-1 , 0
       0     .06       0    32.5     .12       0  120.28     .06       0
  421.73    .016       0   445.2    .045       0   481.3    .016       0
   503.5     .06       0  729.35     .12       0  774.21    .016       0
  840.95     .06       0  945.14     .12       0  1039.9     .06       0
#XS Ineff= 2 , 0
           354.1 2418.78
Permanent Ineff=
       F       F
Bank Sta=445.2,481.3
XS Rating Curve= 0 ,0
Exp/Cntr=0.3,0.1

Type RM Length L Ch R = 1 ,10493.8 ,371,361.8,340.8
XS GIS Cut Line= 3
     2147868.338      205971.596      2147613.13      206414.304
     2147481.186      206678.193
#Sta/Elev= 30
       0 2437.74      36 2430.27    55.7 2427.25    72.1 2421.02    85.2 2418.94
   108.1 2413.13   173.6 2403.52   258.8 2396.49   330.8 2395.21   366.9 2395.55
     380 2394.48   425.8 2395.24   432.4 2393.76   442.2 2393.02   465.1 2395.18
   491.4 2397.53   527.4 2398.68   537.2 2400.29  542.922402.776   553.6 2404.96
  569.352405.416   589.7  2404.2  602.372405.762   655.32411.122   661.8 2412.12
   684.7 2412.26   701.1 2417.07   733.9 2419.23  756.332421.684     806 2427.27
#Mann= 8 ,-1 , 0
       0     .06       0   425.8    .045       0   465.1     .06       0
  542.92    .016       0  569.35     .08       0  602.37     .06       0
   655.3     .12       0  756.33     .06       0
Bank Sta=425.8,465.1
XS Rating Curve= 0 ,0
Exp/Cntr=0.3,0.1

Type RM Length L Ch R = 1 ,10132   ,364,356.1,345.5
XS GIS Cut Line= 2
     2147479.964      205854.089     2147339.465      206595.445
#Sta/Elev= 30
       0 2455.86     9.8 2453.18    39.4 2449.24    65.6 2442.06   111.5 2426.69
   124.7 2418.93   147.6 2410.82     164  2405.7   183.7 2401.68   239.5 2396.64
   354.3 2392.98  368.812393.376   370.7 2393.29   390.4 2391.11   403.4 2393.36
  412.842393.158   442.9 2392.42     456 2393.54   482.3  2393.6   528.2 2397.54
   606.9  2409.3   616.8 2406.19  623.282407.238  653.342407.546     666 2415.91
   669.3 2416.96   708.6 2418.46   719.2 2420.34  743.532421.889   754.6  2422.6
#Mann= 9 ,-1 , 0
       0     .06       0  368.81     .12       0   370.7    .045       0
   403.4     .12       0  412.84     .06       0  623.28    .016       0
  653.34     .06       0   719.2     .12       0  743.53     .06       0
Bank Sta=370.7,403.4
XS Rating Curve= 0 ,0
Exp/Cntr=0.3,0.1

Type RM Length L Ch R = 1 ,9776    ,239.3,256,271.5
XS GIS Cut Line= 2
     2147064.772      205797.319     2147104.051      206544.431
#Sta/Elev= 30
       0 2444.29    32.7 2443.03    45.7 2440.95      49 2440.26    55.5 2436.66
    78.4 2431.64   107.8  2422.2   140.5 2413.86   166.6 2408.51     196 2403.95
   297.3 2393.26  361.142391.337   362.6  2391.2     379 2389.43     392 2391.16
   398.6 2391.89   421.4 2391.29   431.2 2392.45  447.45 2392.52   480.2 2393.14
   535.8 2397.66   601.1 2401.69  645.422407.293  674.782410.543   682.8 2409.15
  699.632409.772   715.5  2408.6   718.7 2409.17  729.212414.301   748.1 2419.06
#Mann= 9 ,-1 , 0
       0     .06       0  361.14     .12       0   362.6    .045       0
     392     .12       0  447.45     .06       0  645.42     .12       0
  674.78    .016       0  699.63     .08       0  729.21     .06       0
Bank Sta=362.6,392
XS Rating Curve= 0 ,0
Exp/Cntr=0.3,0.1

Type RM Length L Ch R = 1 ,9520    ,295.6,289.7,276.6
XS GIS Cut Line= 2
     2146999.383      205780.722     2146712.088      206468.124
#Sta/Elev= 30
       0 2437.99     9.8 2437.39    29.4 2434.93    55.6 2428.52    71.9 2425.59
      98 2419.98   127.4 2414.58   156.8 2410.48   235.3 2401.54     268 2399.24
   297.4 2396.45     317 2393.55   336.6 2389.69   369.2 2391.19     379 2390.69
   388.8 2389.04   392.1 2388.91   401.9 2389.36   411.7 2390.97   428.1  2391.6
  455.07 2391.83  455.25 2391.84  523.042393.042   542.4 2394.04   558.8  2395.5
   578.4 2399.73   604.5 2402.02   705.8 2402.79   725.4  2403.6     745 2405.29
#Mann= 6 ,-1 , 0
       0     .06       0     379    .045       0   411.7     .12       0
  455.07     .06       0  455.25     .12       0  523.04     .06       0
Bank Sta=379,411.7
XS Rating Curve= 0 ,0
Exp/Cntr=0.3,0.1

Type RM Length L Ch R = 1 ,9230.3  ,317.5,305.1,285.6
XS GIS Cut Line= 2
     2146675.769      205712.544     2146562.909      206455.248
#Sta/Elev= 30
       0 2417.64    75.4 2411.14     105 2407.64   137.8 2404.46   226.4 2397.97
   255.9 2394.87     269 2392.68   305.1 2391.09   318.2 2389.51   331.3 2389.37
   334.6 2388.92   341.2 2386.95   347.7 2386.91   370.7 2388.94  394.922389.145
   416.6 2390.09   442.9 2389.94  462.372392.681   472.4 2394.24   505.2 2396.16
  515.082397.827   521.6 2398.84   528.2 2399.14   551.1 2399.38   603.6 2401.02
   610.2 2400.78   616.7 2399.36   656.1 2404.07   731.6 2409.17   751.2 2409.82
#Mann= 6 ,-1 , 0
       0     .06       0   334.6    .045       0   370.7     .12       0
  394.92     .06       0  462.37     .12       0  515.08     .06       0
Bank Sta=334.6,370.7
XS Rating Curve= 0 ,0
Exp/Cntr=0.3,0.1

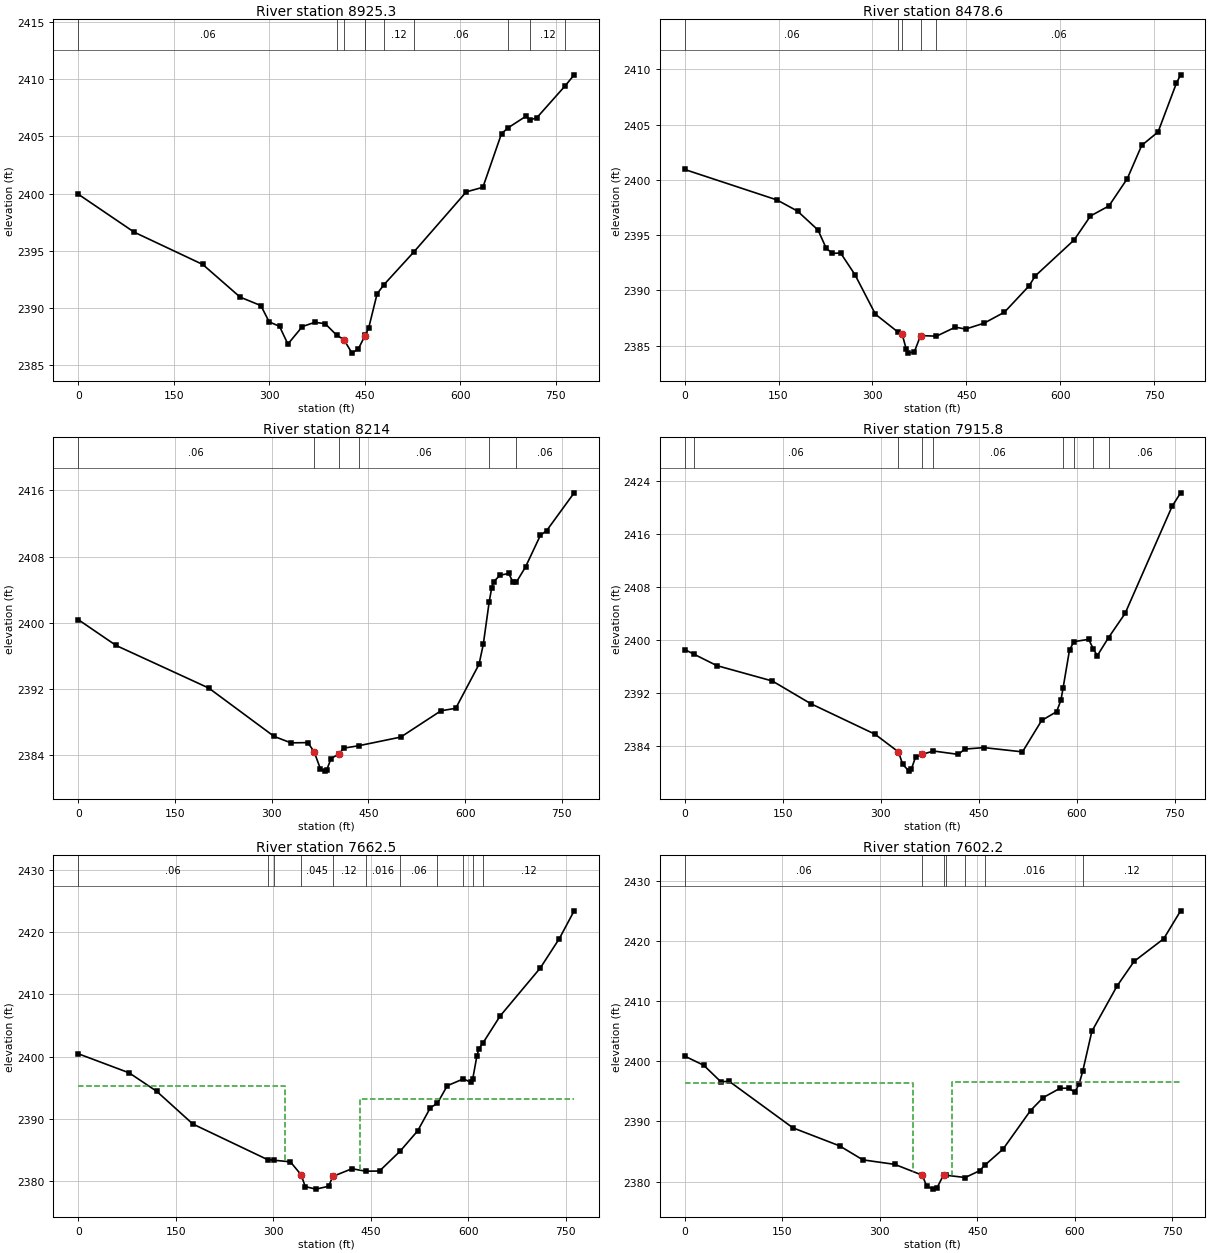
Type RM Length L Ch R = 1 ,8925.3  ,461.2,446.7,425.4
XS GIS Cut Line= 3
     2146226.289      205726.535     2146376.372      206087.934
     2146500.874      206455.259
#Sta/Elev= 30
       0 2399.95      88 2396.63   195.7 2393.81   254.4 2390.96     287 2390.22
     300  2388.8   316.3 2388.41   329.4 2386.86   352.2 2388.39   371.8 2388.76
   388.1 2388.64  405.832387.649   417.4 2387.25   430.2 2386.07   440.2 2386.45
     450 2387.53  451.022387.625   456.5 2388.29   469.6 2391.25   480.52392.055
  527.622394.921   609.7 2400.15   635.8 2400.55   665.1 2405.24  676.042405.767
   704.2 2406.78  709.222406.419   720.5 2406.62  765.482409.434   779.2 2410.37
#Mann= 10 ,-1 , 0
       0     .06       0  405.83     .12       0   417.4    .045       0
     450     .12       0  451.02     .06       0   480.5     .12       0
  527.62     .06       0  676.04     .08       0  709.22     .12       0
  765.48     .06       0
Bank Sta=417.4,450
XS Rating Curve= 0 ,0
Exp/Cntr=0.3,0.1

Type RM Length L Ch R = 1 ,8478.6  ,250.5,264.5,274.2
XS GIS Cut Line= 3
     2145762.589      205920.659     2146008.987      206183.883
     2146309.311      206494.165
#Sta/Elev= 30
       0 2400.94   147.5 2398.18   180.3 2397.17     213 2395.46   226.2  2393.8
     236 2393.34   249.1 2393.38     272 2391.42   304.8 2387.83   341.12386.203
   347.4 2386.04     354 2384.67   357.3 2384.31   367.1 2384.45   376.9  2385.9
  402.262385.845   432.5 2386.66   448.9 2386.49   478.3 2387.02     511 2388.02
   550.3  2390.4   560.1  2391.3   622.3 2394.56   648.4 2396.73   677.9 2397.64
   707.3 2400.12   730.2 2403.12   756.4 2404.34   785.8 2408.77   792.4 2409.51
#Mann= 5 ,-1 , 0
       0     .06       0   341.1     .12       0   347.4    .045       0
   376.9     .12       0  402.26     .06       0
Bank Sta=347.4,376.9
XS Rating Curve= 0 ,0
Exp/Cntr=0.3,0.1

Type RM Length L Ch R = 1 ,8214    ,236.4,298.2,293.8
XS GIS Cut Line= 3
     2145695.827      205953.953     2145834.278      206310.012
     2145943.041      206681.317
#Sta/Elev= 30
       0 2400.37    58.8 2397.24   202.4 2392.09   303.7 2386.24   329.8 2385.46
   355.9 2385.49   365.7  2384.4   375.5 2382.31     382 2382.04   385.3 2382.19
   391.9 2383.55     405 2384.17   411.5 2384.82  434.722385.109   500.1 2386.16
   562.4 2389.34   585.3 2389.64   621.4 2394.96     628 2397.37  637.262402.559
   641.1 2404.22   644.3 2404.98   654.2 2405.75   667.3 2405.95   673.8 2404.98
   679.12404.879   693.5 2406.74   716.5 2410.56   726.3 2411.14   768.9 2415.71
#Mann= 6 ,-1 , 0
       0     .06       0   365.7    .045       0     405     .12       0
  434.72     .06       0  637.26    .016       0   679.1     .06       0
Bank Sta=365.7,405
XS Rating Curve= 0 ,0
Exp/Cntr=0.3,0.1

Type RM Length L Ch R = 1 ,7915.8  ,201,253.3,257.4
XS GIS Cut Line= 2
     2145623.547      205988.957     2145595.932       206747.69
#Sta/Elev= 30
       0 2398.59   13.662397.914    49.1 2396.17   134.2 2393.85   193.1 2390.43
   291.3 2385.84   327.3 2383.17   333.8 2381.28   343.6 2380.28   346.9 2380.56
   353.4 2382.38   363.2 2382.79  380.792383.309   418.9  2382.8   428.7  2383.6
   458.2 2383.82   517.1 2383.18   546.5 2387.91   569.4 2389.23     576 2390.98
  579.372392.853   589.1 2398.51   595.92399.777   618.5 2400.12  625.452398.693
   631.6 2397.66  648.962400.396   674.2 2404.02   746.2 2420.15   759.2 2422.18
#Mann= 9 ,-1 , 0
       0     .12       0   13.66     .06       0   327.3    .045       0
   363.2     .12       0  380.79     .06       0  579.37     .12       0
   595.9    .016       0  625.45     .12       0  648.96     .06       0
Bank Sta=327.3,363.2
XS Rating Curve= 0 ,0
Exp/Cntr=0.3,0.1

Type RM Length L Ch R = 1 ,7662.5  ,89.6,60.3,43.9
XS GIS Cut Line= 3
     2145498.547      206034.096     2145389.172      206544.513
     2145352.713       206782.36
#Sta/Elev= 30
       0 2400.47    78.3  2397.4   120.7 2394.43   176.2 2389.18  291.082383.455
  301.152383.351   326.2  2383.1   342.6 2381.04   349.1 2379.12   365.4 2378.71
     385 2379.17   391.5 2380.75   420.9 2381.99  442.182381.589   463.3 2381.62
  494.952384.808     522 2388.08   541.5 2391.79  552.252392.499   567.5 2395.33
  592.282396.427   603.3  2395.9  606.672396.421     613 2400.09   616.3 2401.31
  622.162402.164   648.8 2406.54   710.6 2414.26   739.9 2418.99   762.6 2423.44
#Mann= 11 ,-1 , 0
       0     .06       0  291.08     .12       0  301.15    .016       0
   342.6    .045       0   391.5     .12       0  442.18    .016       0
  494.95     .06       0  552.25    .016       0  592.28     .06       0
  606.67     .08       0  622.16     .12       0
#XS Ineff= 2 , 0
          317.78 2395.33   433.8         2393.19
Permanent Ineff=
       F       F
Bank Sta=342.6,391.5
XS Rating Curve= 0 ,0
Exp/Cntr=0.3,0.1

Type RM Length L Ch R = 1 ,7602.2  ,263.6,265.5,257.3
XS GIS Cut Line= 3
     2145451.672      206044.513     2145342.297      206554.929
     2145305.838      206792.776
#Sta/Elev= 30
       0 2400.88    29.4 2399.35    55.5 2396.62    68.5 2396.68   166.4 2388.94
   238.2 2385.94     274 2383.61     323 2382.86   365.4 2381.06   371.9 2379.28
   381.7 2378.74   388.2    2379     398 2381.09  402.18 2381.05  431.352380.672
   453.5  2381.8  461.562382.727   489.4 2385.38   531.8 2391.82   551.3 2393.98
   577.3 2395.53   590.3 2395.54     600 2394.85   606.6 2396.26  612.222398.431
   626.1    2405   665.1 2412.59   691.1 2416.65   736.6 2420.41   762.6 2425.06
#Mann= 7 ,-1 , 0
       0     .06       0   365.4    .045       0     398     .12       0
  402.18     .06       0  431.35     .12       0  461.56    .016       0
  612.22     .12       0
#XS Ineff= 2 , 0
          351.07 2396.33   411.6         2396.63
Permanent Ineff=
       F       F
Bank Sta=365.4,398
XS Rating Curve= 0 ,0
Exp/Cntr=0.3,0.1

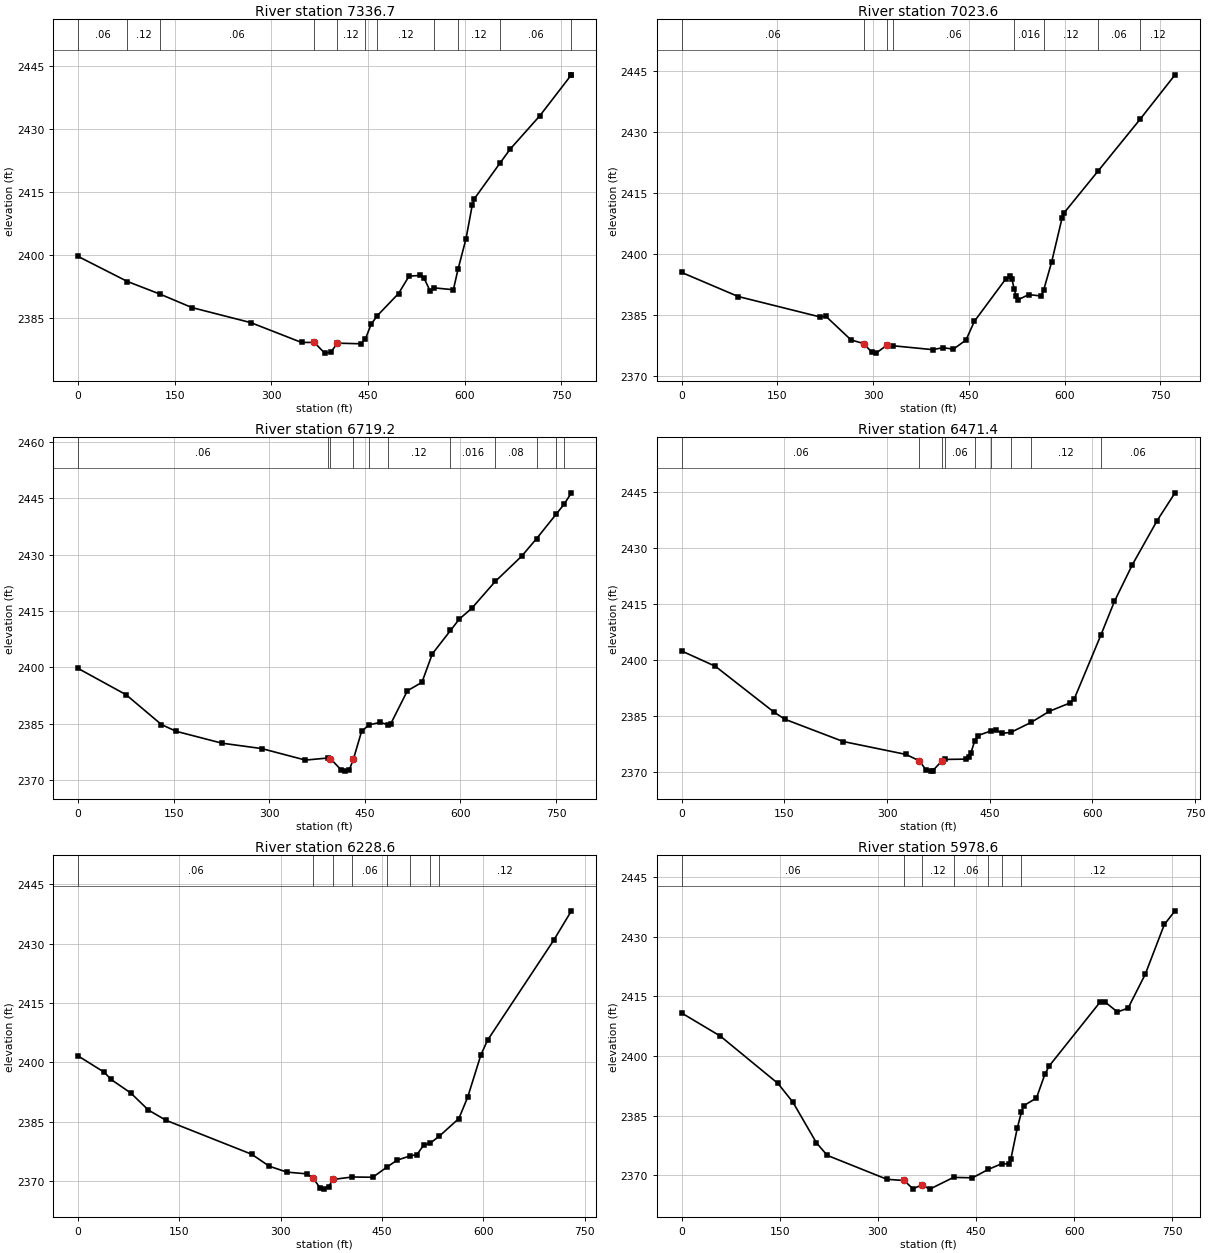
Type RM Length L Ch R = 1 ,7336.7  ,334.7,313.1,283.4
XS GIS Cut Line= 2
     2145208.616      206065.346     2145113.606      206824.999
#Sta/Elev= 30
       0 2399.73   76.592393.757  126.732390.783   176.7 2387.55   268.3 2383.96
   346.8 2379.25   366.4 2379.26   382.8 2376.71   392.6    2377   402.4 2379.08
   438.4 2378.94  445.672379.999   454.8 2383.59  464.622385.663   497.3  2390.9
   513.6 2395.03     530 2395.19   536.6 2394.64   546.4 2391.48  552.882392.237
   582.4  2391.8  589.572396.645     602 2403.92   611.8 2412.05   615.1 2413.48
  654.472421.883   670.7  2425.3   716.5 2433.19  764.952442.836   765.6 2442.95
#Mann= 11 ,-1 , 0
       0     .06       0   76.59     .12       0  126.73     .06       0
   366.4    .045       0   402.4     .12       0  445.67     .06       0
  464.62     .12       0  552.88    .016       0  589.57     .12       0
  654.47     .06       0  764.95     .12       0
Bank Sta=366.4,402.4
XS Rating Curve= 0 ,0
Exp/Cntr=0.3,0.1

Type RM Length L Ch R = 1 ,7023.6  ,298.6,304.4,309.5
XS GIS Cut Line= 2
     2144729.449      206155.624      2145096.96      206835.921
#Sta/Elev= 30
       0 2395.45    88.5 2389.53   216.2 2384.52   226.1 2384.64   265.4 2378.83
     285 2377.95   298.2 2375.77   304.7 2375.58   321.1 2377.48  330.512377.405
   393.2 2376.44   409.5 2376.91   425.9 2376.57   445.6 2378.81   458.7 2383.41
   507.8 2393.84   514.4 2394.46   517.7 2393.73  520.922391.479   524.2 2389.65
   527.5 2388.74   543.9    2390   563.5 2389.65  567.332391.118   579.9 2398.08
   596.3 2408.97   599.6  2410.2  652.452420.409  718.342433.176   773.2 2444.14
#Mann= 8 ,-1 , 0
       0     .06       0     285    .045       0   321.1     .12       0
  330.51     .06       0  520.92    .016       0  567.33     .12       0
  652.45     .06       0  718.34     .12       0
Bank Sta=285,321.1
XS Rating Curve= 0 ,0
Exp/Cntr=0.3,0.1

Type RM Length L Ch R = 1 ,6719.2  ,230.3,247.8,267.2
XS GIS Cut Line= 3
     2144550.844      206221.776      2144709.18       206609.68
     2144867.181      206927.876
#Sta/Elev= 30
       0 2399.69    75.3 2392.69   130.9 2384.73   153.8 2382.95   225.8 2379.78
     288 2378.35   356.8 2375.28  391.652375.826   396.1  2375.7   412.4 2372.71
     419 2372.34   425.5 2372.63     432  2375.5     445 2382.98  456.692384.645
   474.4 2385.35  486.34 2384.65   490.7 2384.95   516.8 2393.74   539.6 2395.98
   555.9 2403.57   584.4 2409.79   598.2 2412.82   617.8  2415.7  654.572422.837
     696 2429.56  719.512434.251  750.562440.834  762.432443.347   774.2 2446.45
#Mann= 11 ,-1 , 0
       0     .06       0  391.65     .12       0   396.1    .045       0
     432     .12       0  456.69    .016       0  486.34     .12       0
   584.4    .016       0  654.57     .08       0  719.51     .06       0
  750.56     .12       0  762.43     .06       0
Bank Sta=396.1,432
XS Rating Curve= 0 ,0
Exp/Cntr=0.3,0.1

Type RM Length L Ch R = 1 ,6471.4  ,236,242.8,248.3
XS GIS Cut Line= 2
     2144491.346      206222.402     2144453.408      206942.082
#Sta/Elev= 30
       0 2402.39    49.1  2398.3   134.3 2386.08   150.7 2384.09   235.9 2378.12
   327.6 2374.66   347.2 2372.94   357.1 2370.47   363.6 2370.18   366.9 2370.34
     380 2372.87  384.592373.315     416  2373.4   419.3 2373.87   422.6 2375.16
  427.992378.219   432.4  2379.7  451.192380.916   458.6 2381.16   468.4 2380.32
  480.772380.563  510.862383.289   537.2 2386.23   566.7 2388.42   573.3 2389.47
  612.342406.646   632.2 2415.71   658.4 2425.54   694.5 2437.33   720.7  2444.8
#Mann= 9 ,-1 , 0
       0     .06       0   347.2    .045       0     380     .12       0
  384.59     .06       0  427.99    .016       0  451.19     .08       0
  480.77     .06       0  510.86     .12       0  612.34     .06       0
Bank Sta=347.2,380
XS Rating Curve= 0 ,0
Exp/Cntr=0.3,0.1

Type RM Length L Ch R = 1 ,6228.6  ,264.5,250,239.1
XS GIS Cut Line= 3
     2144321.609      206195.272     2144238.224      206549.994
     2144156.103      206906.412
#Sta/Elev= 30
       0 2401.61      39 2397.45    48.8 2395.66    78.1 2392.22   104.1 2387.92
   130.1 2385.34     257 2376.75     283 2373.73   309.1 2372.24   338.4  2371.8
   348.1 2370.68   357.9  2368.3   364.4 2367.94   370.9  2368.6   377.4 2370.39
   405.92371.008   436.2 2370.94  457.122373.512   472.2 2375.26  490.572376.289
   501.6 2376.68   511.4 2379.04  520.882379.526  534.542381.308   563.6 2385.78
   576.7  2391.2   596.2 2401.87     606 2405.56     704 2430.85   730.2 2438.28
#Mann= 8 ,-1 , 0
       0     .06       0   348.1    .045       0   377.4     .12       0
   405.9     .06       0  457.12    .016       0  490.57     .08       0
  520.88     .06       0  534.54     .12       0
Bank Sta=348.1,377.4
XS Rating Curve= 0 ,0
Exp/Cntr=0.3,0.1

Type RM Length L Ch R = 1 ,5978.6  ,235.6,250,257.3
XS GIS Cut Line= 3
     2143933.719      206163.103     2143994.032      206517.709
     2144084.076      206901.579
#Sta/Elev= 30
       0 2410.78    58.9    2405   147.2 2393.07     170 2388.36     206 2378.15
   222.4 2375.01   313.9 2368.98   340.1 2368.69   353.2 2366.61   367.2 2367.55
   379.2 2366.52  415.442369.473   444.4 2369.36  468.612371.475  488.792372.888
   499.8 2372.87   503.1 2374.08   512.8  2381.8  519.132385.804   522.6 2387.49
   542.2 2389.41   555.2 2395.44   561.7 2397.48   639.9 2413.62   646.4 2413.64
     666 2411.04   682.3 2412.03   708.4 2420.49   737.7 2433.05     754 2436.47
#Mann= 7 ,-1 , 0
       0     .06       0   340.1    .045       0   367.2     .12       0
  415.44     .06       0  468.61    .016       0  488.79     .08       0
  519.13     .12       0
Bank Sta=340.1,367.2
XS Rating Curve= 0 ,0
Exp/Cntr=0.3,0.1