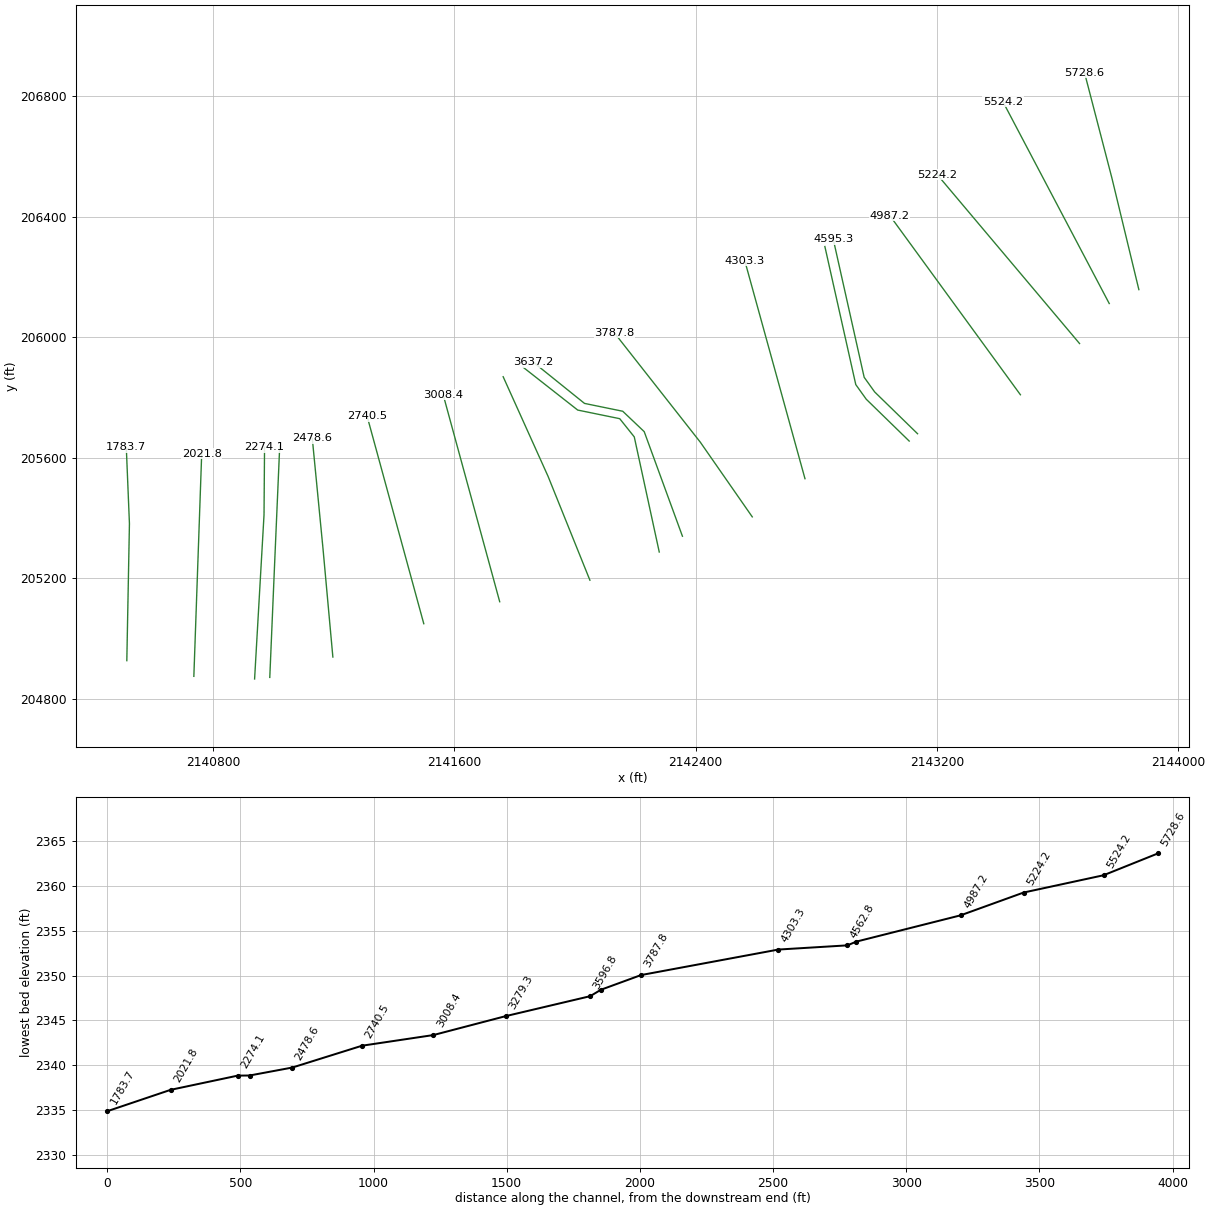
HEC-RAS study KITCHENCK.prj: KITCHENCK

--- KITCHENCK.g01 (geometry) --- (continued)

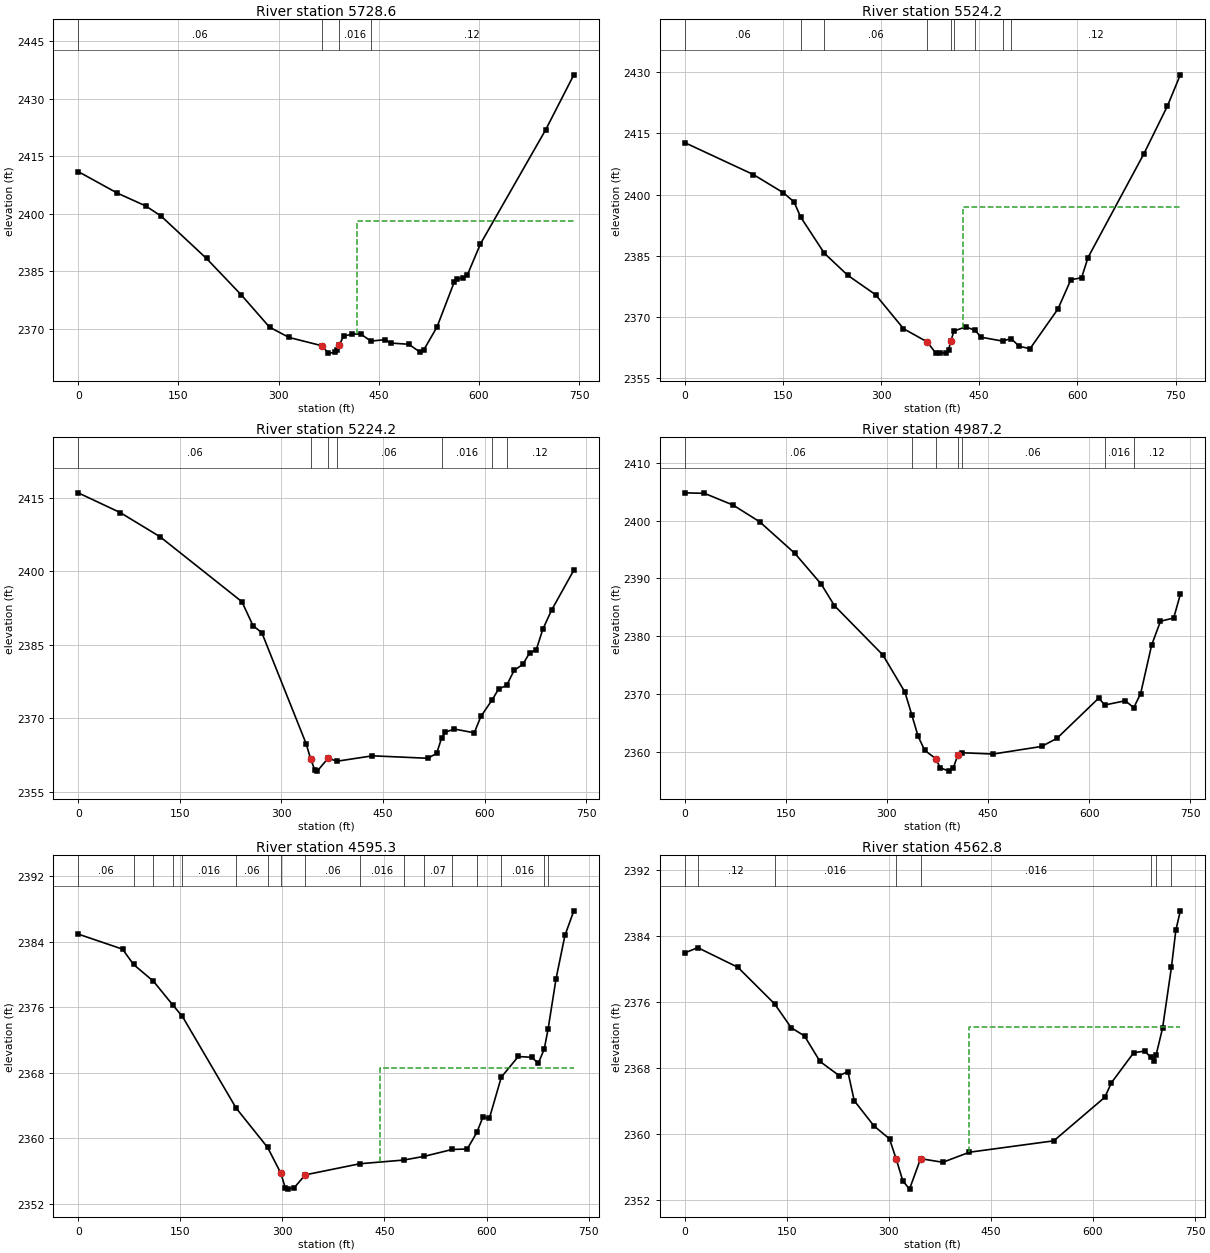
Type RM Length L Ch R = 1 ,5728.6  ,194.9,204.3,212.9
XS GIS Cut Line= 3
     2143869.329      206158.448     2143779.946      206528.998
     2143689.211      206878.517
#Sta/Elev= 30
       0 2411.01    58.6 2405.39     101 2402.05   123.8 2399.45   192.2 2388.33
   244.4  2378.8   286.7 2370.39     316 2367.72   364.9 2365.57   374.7 2363.64
   384.4 2363.82   387.7 2364.33   390.9 2365.75   397.4 2368.03   410.5 2368.64
   423.5 2368.59  438.312366.781   459.2 2367.14     469 2366.26     495 2365.95
   511.3    2364   517.8 2364.56   537.3 2370.43   563.4 2382.28   566.6 2383.05
   576.4  2383.2   582.9 2384.06   602.4 2392.13     700 2421.87   742.3 2436.25
#Mann= 4 ,-1 , 0
       0     .06       0   364.9    .045       0   390.9    .016       0
  438.31     .12       0
#XS Ineff= 2 , 0
                          417.65         2398.06
Permanent Ineff=
       F       F
Bank Sta=364.9,390.9
XS Rating Curve= 0 ,0
Exp/Cntr=0.3,0.1

Type RM Length L Ch R = 1 ,5524.2  ,288.6,300,308.8
XS GIS Cut Line= 2
     2143771.116      206112.221     2143418.686       206782.36
#Sta/Elev= 30
       0 2412.74   104.9 2404.92   150.8 2400.46   167.2  2398.2  177.112394.533
  213.292385.675   249.1 2380.26   291.7  2375.5   334.3 2367.19   370.4 2363.96
   383.5 2361.24     390  2361.2   399.9 2361.27   403.2 2361.96   406.4 2364.08
  411.522366.624   429.4 2367.62  444.172366.767   452.3 2365.11  485.772364.148
  498.612364.764   511.3 2362.85   527.7  2362.3   570.3 2372.01     590 2379.18
   606.4 2379.64   616.2  2384.6   701.4 2409.95   737.5 2421.68   757.2 2429.33
#Mann= 9 ,-1 , 0
       0     .06       0  177.11     .12       0  213.29     .06       0
   370.4    .045       0   406.4     .12       0  411.52    .016       0
  444.17     .12       0  485.77     .06       0  498.61     .12       0
#XS Ineff= 2 , 0
                          425.73         2397.05
Permanent Ineff=
       F       F
Bank Sta=370.4,406.4
XS Rating Curve= 0 ,0
Exp/Cntr=0.3,0.1

Type RM Length L Ch R = 1 ,5224.2  ,239.4,237,234
XS GIS Cut Line= 2
      2143672.73      205979.391     2143201.672      206539.304
#Sta/Elev= 30
       0    2416    62.1 2411.97   120.9 2407.04   241.7  2393.8   258.1 2388.92
   271.1 2387.48   336.5 2364.86     343 2361.83   349.5 2359.41   352.8 2359.27
   369.1 2361.92  381.882361.285   434.4 2362.39   516.1 2361.89   529.2 2362.89
  536.682366.082   542.2 2367.21   555.3 2367.85   584.7 2367.08   594.5 2370.42
  611.322373.838   620.6    2376  632.452376.739   643.5 2379.79   656.6 2381.06
   666.4 2383.38   676.2    2384     686 2388.22     699 2392.13   731.7 2400.24
#Mann= 7 ,-1 , 0
       0     .06       0     343    .045       0   369.1     .12       0
  381.88     .06       0  536.68    .016       0  611.32     .06       0
  632.45     .12       0
Bank Sta=343,369.1
XS Rating Curve= 0 ,0
Exp/Cntr=0.3,0.1

Type RM Length L Ch R = 1 ,4987.2  ,409.3,391.9,369.3
XS GIS Cut Line= 2
     2143476.639       205809.34     2143044.049      206403.704
#Sta/Elev= 30
       0 2404.79    29.4  2404.7    71.9 2402.67   111.1  2399.8   163.4 2394.34
   202.6 2389.01   222.2 2385.29     294 2376.78   326.7 2370.36  336.93 2366.41
   346.3 2362.71   356.1  2360.3   372.5 2358.87     379  2357.3   392.1 2356.72
   398.6 2357.33   405.1 2359.49  410.76  2359.9   457.4 2359.67   529.3 2360.98
   552.2 2362.39   614.2 2369.34  622.972368.142   653.4 2368.87  666.142367.691
   676.3 2370.12   692.6  2378.5   705.7 2382.61   725.3 2383.17   735.1 2387.23
#Mann= 7 ,-1 , 0
       0     .06       0  336.93     .12       0   372.5    .045       0
   405.1     .12       0  410.76     .06       0  622.97    .016       0
  666.14     .12       0
Bank Sta=372.5,405.1
XS Rating Curve= 0 ,0
Exp/Cntr=0.3,0.1

Type RM Length L Ch R = 1 ,4595.3  ,32.4,32.5,34.6
XS GIS Cut Line= 4
     2143135.699      205679.929     2142993.338      205818.818
     2142958.616      205867.429     2142856.186      206325.763
#Sta/Elev= 30
       0 2384.91    65.2 2383.07    81.32381.201  110.612379.153  138.762376.278
  153.162374.854  232.022363.677  278.362358.863   297.8 2355.72   304.3 2353.92
   307.6 2353.78   317.3 2353.94   333.6 2355.52  413.852356.878  478.572357.331
  508.832357.789  549.332358.618   571.7 2358.68  585.722360.694   594.6 2362.55
   604.3 2362.45  621.722367.447   646.7 2369.97   666.3 2369.87   676.1 2369.15
  684.812370.873  690.432373.296   702.2 2379.47   715.2 2384.74   728.3 2387.75
#Mann= 17 ,-1 , 0
       0     .06       0    81.3     .12       0  110.61    .016       0
  138.76     .06       0  153.16    .016       0  232.02     .06       0
  278.36    .016       0   297.8    .045       0   333.6     .06       0
  413.85    .016       0  478.57     .06       0  508.83     .07       0
  549.33    .016       0  585.72     .06       0  621.72    .016       0
  684.81     .08       0  690.43     .12       0
#XS Ineff= 2 , 0
                          442.88         2368.57
Permanent Ineff=
       F       F
Bank Sta=297.8,333.6
XS Rating Curve= 0 ,0
Exp/Cntr=0.3,0.1

Type RM Length L Ch R = 1 ,4562.8  ,256.8,259.5,260.8
XS GIS Cut Line= 4
     2143107.922      205655.624     2142965.561      205794.513
     2142930.838      205843.124     2142828.408      206301.457
#Sta/Elev= 30
       0 2381.98   19.282382.619    78.2 2380.24  132.05 2375.82   156.5 2372.93
   176.1 2371.92   198.9 2368.83   227.2 2367.11   239.8 2367.61   249.2 2364.08
   278.2 2361.02     301 2359.46   310.8 2357.02   320.6 2354.37   330.4 2353.37
   346.7 2357.06   379.3 2356.62   418.4 2357.84   542.4 2359.22   617.4  2364.5
   627.2 2366.27   659.8 2369.89   676.1 2370.09  685.062369.315   689.1 2368.92
  692.882369.666   702.2 2372.85  715.332380.272   721.7  2384.7   728.3 2387.08
#Mann= 8 ,-1 , 0
       0     .06       0   19.28     .12       0  132.05    .016       0
   310.8    .045       0   346.7    .016       0  685.06     .08       0
  692.88     .06       0  715.33     .12       0
#XS Ineff= 2 , 0
                          417.65         2372.96
Permanent Ineff=
       F       F
Bank Sta=310.8,346.7
XS Rating Curve= 0 ,0
Exp/Cntr=0.3,0.1

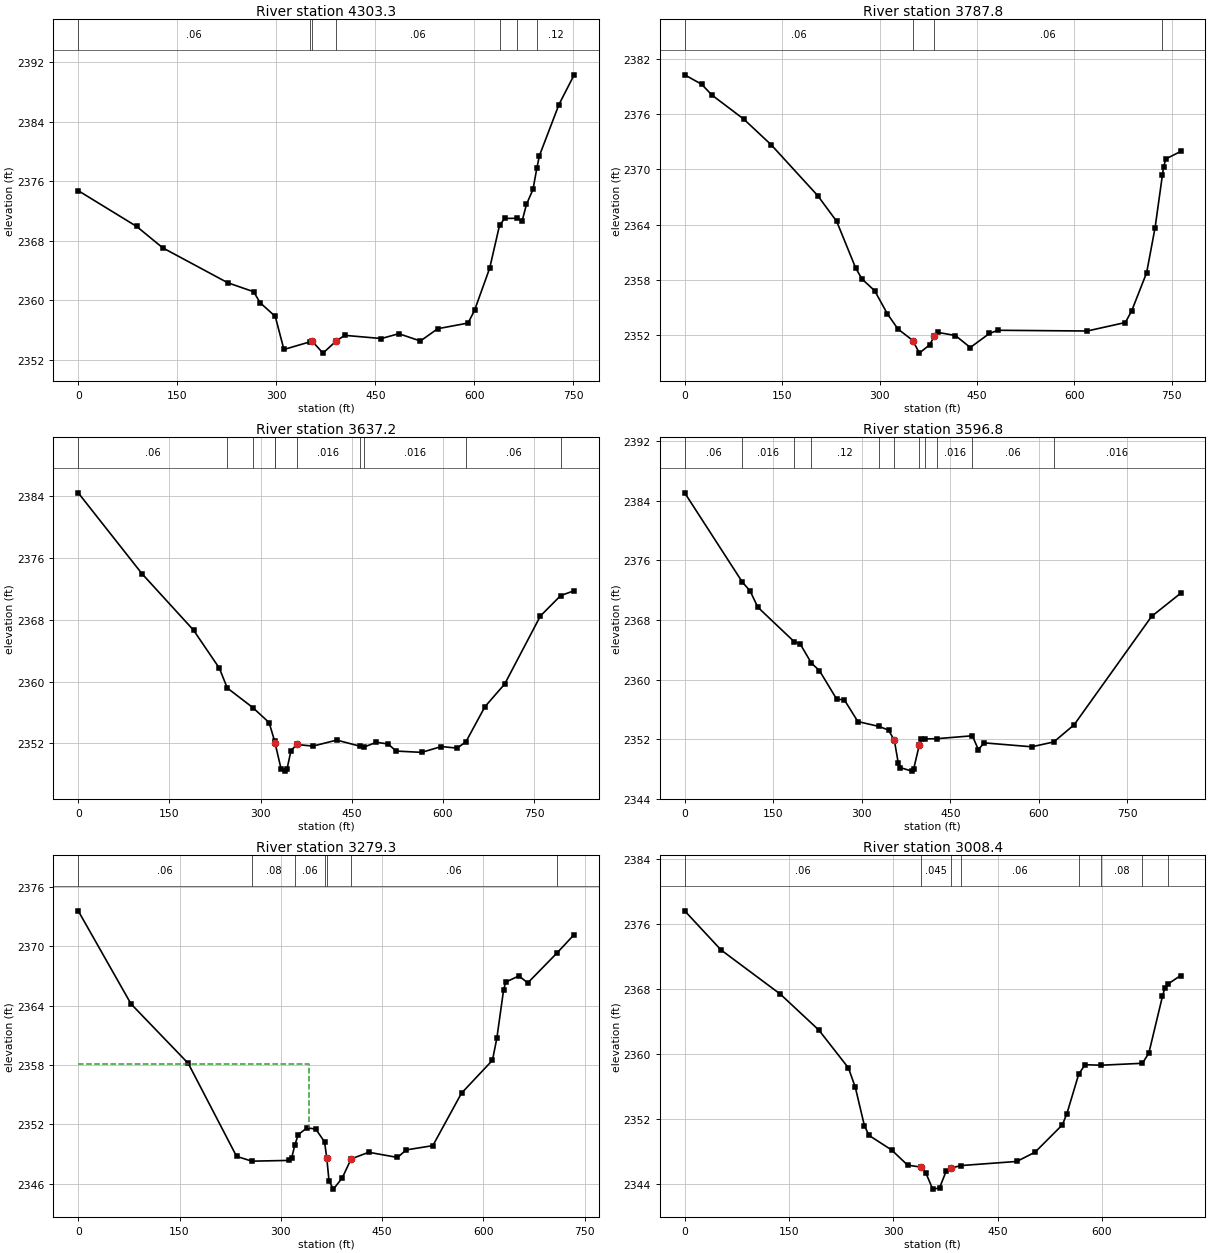
Type RM Length L Ch R = 1 ,4303.3  ,482.4,515.5,502.7
XS GIS Cut Line= 2
     2142762.436      205530.624     2142562.783      206254.582
#Sta/Elev= 30
       0 2374.73    88.5 2369.92   127.9 2367.05   226.3 2362.36   265.6 2361.15
   275.5 2359.67   298.4 2357.83   311.5 2353.39  350.382354.403   354.2 2354.52
   370.6  2352.9   390.2 2354.49   403.4 2355.29   459.1 2354.86   485.4 2355.51
   518.2 2354.53   544.4 2356.18   590.3 2356.94   600.1 2358.63   623.1 2364.32
  638.092370.107     646 2370.99  663.932371.017   672.3 2370.68   678.8 2372.89
   688.7  2374.9  694.572377.789   698.5 2379.45     728  2386.3     751 2390.29
#Mann= 7 ,-1 , 0
       0     .06       0  350.38     .12       0   354.2    .045       0
   390.2     .06       0  638.09    .016       0  663.93     .08       0
  694.57     .12       0
Bank Sta=354.2,390.2
XS Rating Curve= 0 ,0
Exp/Cntr=0.3,0.1

Type RM Length L Ch R = 1 ,3787.8  ,160.7,150.6,146.3
XS GIS Cut Line= 3
     2142587.695      205403.922     2142415.213      205652.151
     2142130.491      206014.999
#Sta/Elev= 30
       0 2380.25      26 2379.23    42.2 2378.04      91 2375.44   133.3 2372.65
   204.8 2367.14     234 2364.35   263.3 2359.28     273 2358.09   292.5 2356.82
   312.1 2354.31   328.4 2352.66   351.3 2351.42   361.2 2350.05   377.5 2350.97
     384 2351.88   390.6 2352.29   416.8 2351.96   439.7 2350.66   469.1 2352.18
   482.2 2352.53   619.6 2352.45   678.4 2353.37   688.3 2354.66   711.2 2358.78
   724.2 2363.67  735.422369.346   737.3 2370.24   740.6 2371.12   763.5 2371.93
#Mann= 4 ,-1 , 0
       0     .06       0   351.3    .045       0     384     .06       0
  735.42    .016       0
Bank Sta=351.3,384
XS Rating Curve= 0 ,0
Exp/Cntr=0.3,0.1

Type RM Length L Ch R = 1 ,3637.2  ,46.8,40.5,42.4
XS GIS Cut Line= 5
     2142356.186      205339.651     2142229.449      205686.874
     2142158.269      205754.582     2142031.533      205780.624
     2141861.394      205917.776
#Sta/Elev= 30
       0 2384.46   104.7    2374   189.7 2366.67   232.2 2361.74  245.182359.176
  287.172356.643     314  2354.7  323.032352.314   323.8 2352.04   333.6 2348.74
   340.2 2348.41   343.5 2348.69     350 2351.07   359.8 2351.86     386 2351.65
   425.3 2352.43  462.95 2351.65  470.532351.539   490.5 2352.15   509.9 2351.92
   522.9 2351.01   564.9 2350.84   597.2 2351.59   623.4 2351.39  637.922352.228
     669 2356.75   701.6  2359.7   760.3 2368.51  793.542371.142   815.8 2371.78
#Mann= 10 ,-1 , 0
       0     .06       0  245.18    .016       0  287.17     .12       0
  323.03    .016       0   323.8    .045       0   359.8    .016       0
  462.95     .06       0  470.53    .016       0  637.92     .06       0
  793.54    .016       0
Bank Sta=323.8,359.8
XS Rating Curve= 0 ,0
Exp/Cntr=0.3,0.1

Type RM Length L Ch R = 1 ,3596.8  ,310.4,317.5,310.7
XS GIS Cut Line= 5
     2142279.305      205287.206     2142196.463      205669.513
     2142148.228      205729.915     2142008.905      205758.561
     2141828.408      205900.415
#Sta/Elev= 30
       0 2385.09   97.742373.088   110.8 2371.91   123.9 2369.72   185.32365.104
   195.6 2364.79  214.722362.203   228.2 2361.21   257.5 2357.37   270.6 2357.26
   293.4 2354.35  329.682353.688   345.5  2353.2   355.3 2351.82   361.8 2348.82
   365.1 2348.17   384.7 2347.69   387.9 2347.95   397.6 2351.22   400.8 2352.01
  407.392352.021  427.662352.053  487.43 2352.44   497.6 2350.58   507.3 2351.49
   588.1 2350.96  625.492351.616   659.9 2353.92   791.1 2368.48   840.3 2371.59
#Mann= 11 ,-1 , 0
       0     .06       0   97.74    .016       0   185.3     .06       0
  214.72     .12       0  329.68     .06       0   355.3    .045       0
   397.6    .016       0  407.39     .08       0  427.66    .016       0
  487.43     .06       0  625.49    .016       0
Bank Sta=355.3,397.6
XS Rating Curve= 0 ,0
Exp/Cntr=0.3,0.1

Type RM Length L Ch R = 1 ,3279.3  ,275.7,270.9,263.8
XS GIS Cut Line= 3
     2142049.434      205193.571     2141910.869      205538.105
     2141761.841      205869.182
#Sta/Elev= 30
       0 2373.56    78.2 2364.16   162.9 2358.16   234.5 2348.77  257.162348.283
   312.7 2348.36     316 2348.59  320.832349.923   325.8 2350.96   338.8 2351.65
   351.8 2351.52  364.792350.232   368.1 2348.59   371.4 2346.29   377.9 2345.46
     391 2346.59   404.1 2348.51   430.2 2349.18   472.8 2348.66   485.8 2349.42
   525.1 2349.85   567.6 2355.15   613.4 2358.47   619.9 2360.69   629.8 2365.52
     633 2366.36   652.6 2366.99   665.7 2366.28  708.642369.279   734.4 2371.16
#Mann= 7 ,-1 , 0
       0     .06       0  257.16     .08       0  320.83     .06       0
  364.79     .12       0   368.1    .045       0   404.1     .06       0
  708.64    .016       0
#XS Ineff= 2 , 0
          341.99 2358.05
Permanent Ineff=
       F       F
Bank Sta=368.1,404.1
XS Rating Curve= 0 ,0
Exp/Cntr=0.3,0.1

Type RM Length L Ch R = 1 ,3008.4  ,268.3,267.9,266.9
XS GIS Cut Line= 2
     2141750.383      205122.111     2141562.783      205810.138
#Sta/Elev= 30
       0 2377.62    52.3  2372.8   137.4 2367.37     193 2362.93   235.5 2358.27
   245.4 2355.87   258.4 2351.17     265 2349.97   297.7 2348.16   320.6  2346.3
   340.2 2346.06   346.8 2345.34   356.6 2343.35   366.4 2343.48   376.2 2345.61
   382.7 2345.94  397.16 2346.25   477.6 2346.76   503.8  2347.9     543 2351.26
   549.6 2352.65  566.642357.524   575.8 2358.67  598.412358.607  658.112358.845
   667.4  2360.1     687  2367.1   690.2 2368.06  695.212368.624   713.1 2369.65
#Mann= 8 ,-1 , 0
       0     .06       0   340.2    .045       0   382.7     .12       0
  397.16     .06       0  566.64    .016       0  598.41     .08       0
  658.11     .06       0  695.21    .016       0
Bank Sta=340.2,382.7
XS Rating Curve= 0 ,0
Exp/Cntr=0.3,0.1

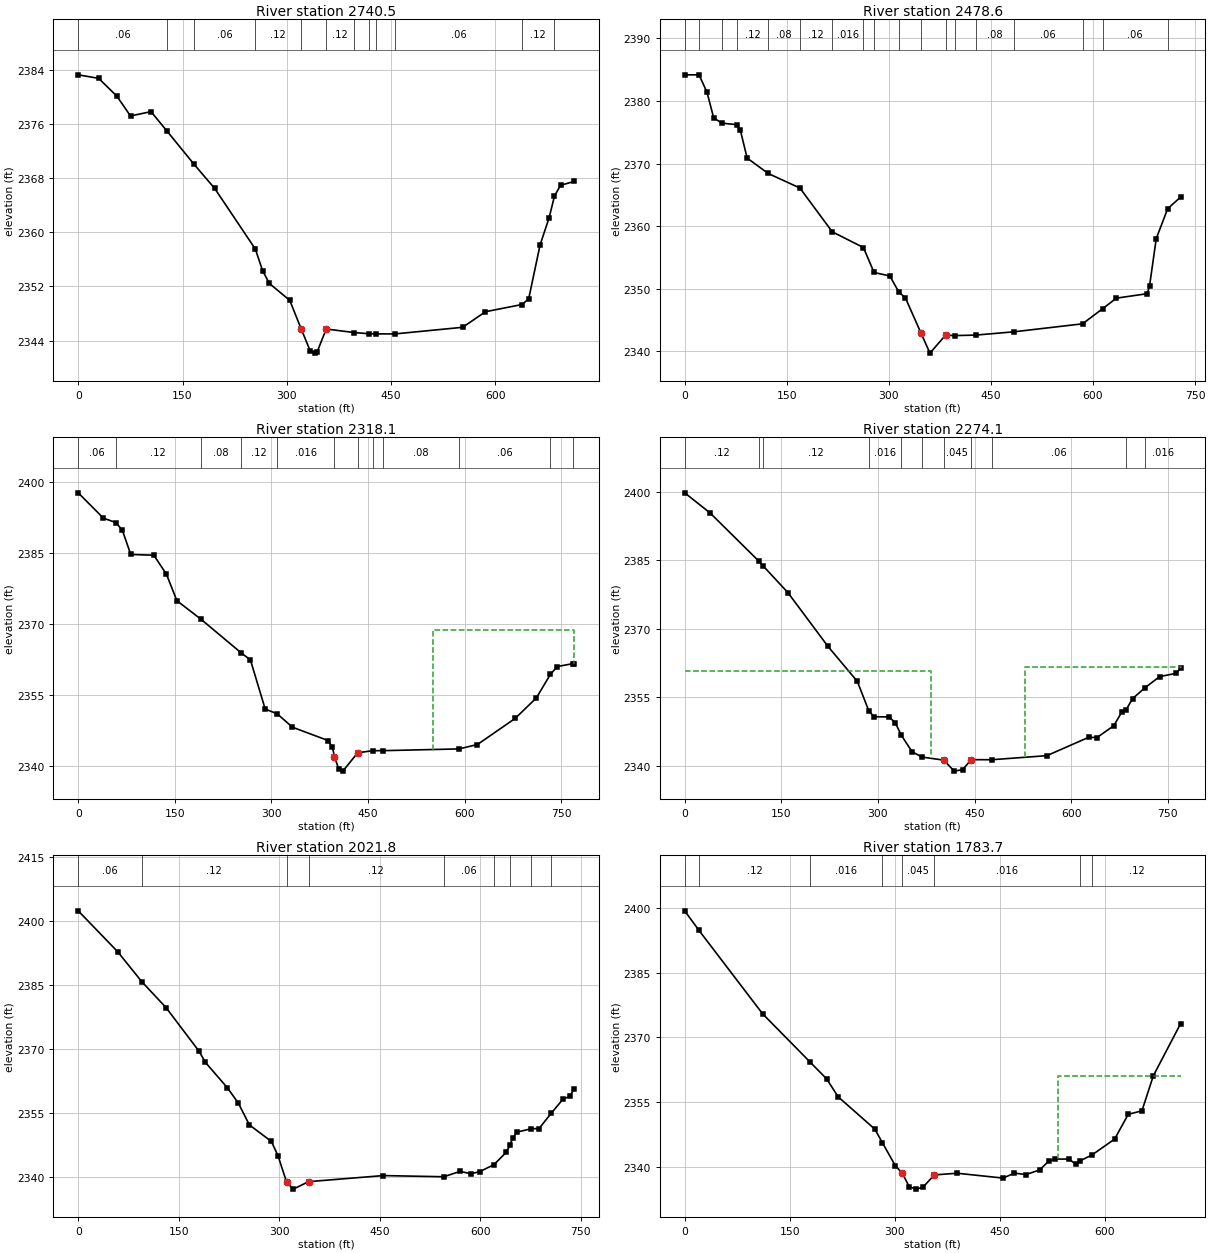
Type RM Length L Ch R = 1 ,2740.5  ,268.3,261.9,255.4
XS GIS Cut Line= 2
     2141498.647      205049.194     2141311.047      205737.221
#Sta/Elev= 30
       0 2383.22    29.4  2382.7    55.6 2380.07    75.2 2377.15   104.7 2377.79
   127.9 2374.89  166.712370.005   196.3 2366.45  254.752357.504     265 2354.35
   274.8 2352.45   304.2 2349.94   320.6 2345.74   333.7 2342.45   340.2 2342.16
   343.5 2342.33   356.6 2345.72  396.892345.193   417.42345.028  427.51    2345
  455.032344.991   552.8 2345.97   585.6 2348.27  638.112349.332   647.7 2350.16
   664.1 2358.12   677.2 2362.16  684.822365.338   693.5 2366.92   713.1 2367.49
#Mann= 12 ,-1 , 0
       0     .06       0   127.9     .12       0  166.71     .06       0
  254.75     .12       0   320.6    .045       0   356.6     .12       0
  396.89     .08       0   417.4     .12       0  427.51     .08       0
  455.03     .06       0  638.11     .12       0  684.82    .016       0
Bank Sta=320.6,356.6
XS Rating Curve= 0 ,0
Exp/Cntr=0.3,0.1

Type RM Length L Ch R = 1 ,2478.6  ,165.4,160.5,155
XS GIS Cut Line= 3
     2141197.265      204938.493     2141164.332      205300.798
     2141129.064      205664.233
#Sta/Elev= 30
       0 2384.18   21.082384.179    32.8  2381.4    42.6 2377.32   54.582376.454
    76.42376.225    81.9  2375.3    91.8 2370.88  122.812368.418  169.372366.093
  216.942359.098  262.732356.589  278.332352.601   301.5 2352.05  314.572349.517
   324.5 2348.52   347.4  2342.9   360.5 2339.72   383.4 2342.59  396.782342.523
  427.452342.599  483.642343.123  584.732344.403  614.412346.824   634.4  2348.5
     680 2349.22   683.3 2350.51   693.1 2358.02  709.882362.798   728.9 2364.65
#Mann= 18 ,-1 , 0
       0     .08       0   21.08     .12       0   54.58    .016       0
    76.4     .12       0  122.81     .08       0  169.37     .12       0
  216.94    .016       0  262.73     .06       0  278.33    .016       0
  314.57     .12       0   347.4    .045       0   383.4     .12       0
  396.78     .06       0  427.45     .08       0  483.64     .06       0
  584.73     .08       0  614.41     .06       0  709.88    .016       0
Bank Sta=347.4,383.4
XS Rating Curve= 0 ,0
Exp/Cntr=0.3,0.1

Type RM Length L Ch R = 1 ,2318.1  ,44.4,44,43.4
XS GIS Cut Line= 3
      2140988.13      204870.901     2141003.755      205238.957
     2141021.116      205639.999
#Sta/Elev= 30
       0 2397.68    39.1 2392.33   58.392391.395    68.5 2389.78    81.5 2384.65
   117.4 2384.48   136.9 2380.48   153.2 2374.86  190.172370.993  252.47 2363.89
   267.3 2362.35   290.2 2351.96     3092350.937   332.5 2348.12     388 2345.29
   394.5 2343.87   397.8 2341.92   404.3 2339.27   410.8 2338.83   433.7  2342.7
  456.962343.153  472.992343.157  591.252343.529   619.7 2344.46   678.4 2349.99
   711.1 2354.31  733.062359.314   743.7 2360.95  768.642361.577   769.8 2361.57
#Mann= 12 ,-1 , 0
       0     .06       0   58.39     .12       0  190.17     .08       0
  252.47     .12       0     309    .016       0   397.8    .045       0
   433.7    .016       0  456.96     .12       0  472.99     .08       0
  591.25     .06       0  733.06    .016       0  768.64     .08       0
#XS Ineff= 2 , 0
                          550.82         2368.57
Permanent Ineff=
       F       F
Bank Sta=397.8,433.7
XS Rating Curve= 0 ,0
Exp/Cntr=0.3,0.1

Type RM Length L Ch R = 1 ,2274.1  ,252.5,252.3,250.2
XS GIS Cut Line= 3
     2140937.783      204865.693     2140969.033      205410.832
     2140970.769       205634.79
#Sta/Elev= 30
       0 2399.82    39.2 2395.44  115.022384.864  121.532383.842   160.2 2377.96
   222.3 2366.19   268.1 2358.48  286.112351.942   294.3 2350.74   317.2  2350.7
     327 2349.43  336.332346.688   353.1 2343.06  368.542341.904   402.2 2341.23
   418.5 2338.82   431.6 2339.14   444.7 2341.33  476.86 2341.32   562.3 2342.21
   627.2 2346.23   640.2 2346.19   666.1 2348.75   679.1 2351.86  685.432352.279
   695.3  2354.7  714.97 2357.13   737.5 2359.54   763.5 2360.27     770 2361.41
#Mann= 11 ,-1 , 0
       0     .12       0  115.02     .06       0  121.53     .12       0
  286.11    .016       0  336.33     .06       0  368.54     .12       0
   402.2    .045       0   444.7     .12       0  476.86     .06       0
  685.43     .08       0  714.97    .016       0
#XS Ineff= 2 , 0
          382.35 2360.71  528.63          2361.7
Permanent Ineff=
       F       F
Bank Sta=402.2,444.7
XS Rating Curve= 0 ,0
Exp/Cntr=0.3,0.1

Type RM Length L Ch R = 1 ,2021.8  ,235,238.1,241.6
XS GIS Cut Line= 2
     2140736.394      204874.374     2140762.436      205613.957
#Sta/Elev= 30
       0 2402.34    58.9 2392.77   94.862385.765     131 2379.71   180.1 2369.53
   189.9 2366.86   222.7 2360.92     239 2357.33   255.4 2352.26   288.2 2348.39
     298 2345.09   311.1  2338.8   320.9 2337.23   343.8 2338.98   455.2  2340.4
  545.492340.124   569.8 2341.38   586.1 2340.83   599.2 2341.32  620.422342.968
   638.5 2345.83  643.982347.442   648.4 2349.22   654.9 2350.58  676.252351.361
   687.6 2351.39   705.82354.983   723.7 2358.34   733.5 2358.91     740 2360.74
#Mann= 9 ,-1 , 0
       0     .06       0   94.86     .12       0   311.1    .045       0
   343.8     .12       0  545.49     .06       0  620.42     .12       0
  643.98    .016       0  676.25     .08       0   705.8     .12       0
Bank Sta=311.1,343.8
XS Rating Curve= 0 ,0
Exp/Cntr=0.3,0.1

Type RM Length L Ch R = 1 ,1783.7  ,34.1,31.6,28.3
XS GIS Cut Line= 3
     2140514.172      204926.457     2140522.852      205381.318
     2140512.436       205634.79
#Sta/Elev= 30
       0 2399.35    20.42394.822   111.3 2375.49  178.942364.333   202.9 2360.38
   219.3 2356.24   271.7 2348.74  282.332345.648   301.1 2340.23   310.9 2338.55
   320.8 2335.41   330.6 2334.84   340.4 2335.28   356.8 2338.14   389.5 2338.52
   454.9  2337.4   471.2 2338.55   487.5 2338.22     507 2339.27     520  2341.3
   529.8  2341.8   549.3 2341.81     559 2340.55  564.822341.376  582.442342.812
   614.3 2346.44   633.8 2352.19   653.3 2352.98   669.6 2361.11   708.6 2373.21
#Mann= 8 ,-1 , 0
       0     .06       0    20.4     .12       0  178.94    .016       0
  282.33     .12       0   310.9    .045       0   356.8    .016       0
  564.82     .06       0  582.44     .12       0
#XS Ineff= 2 , 0
                          533.67         2361.16
Permanent Ineff=
       F       F
Bank Sta=310.9,356.8
XS Rating Curve= 0 ,0
Exp/Cntr=0.3,0.1