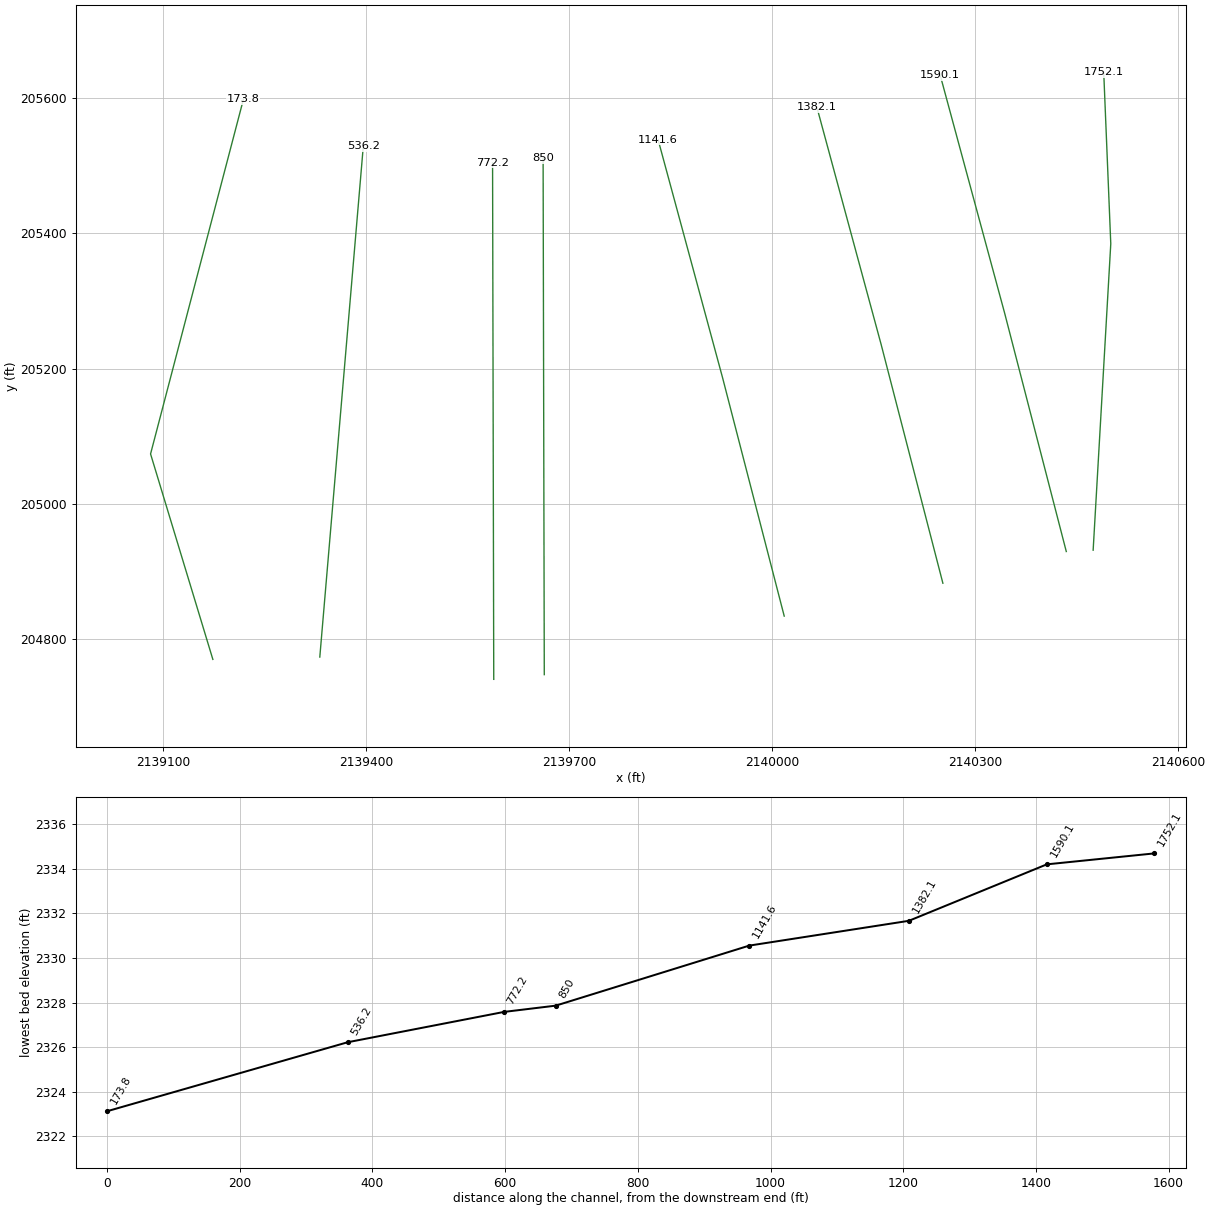
HEC-RAS study KITCHENCK.prj: KITCHENCK

--- KITCHENCK.g01 (geometry) --- (continued)

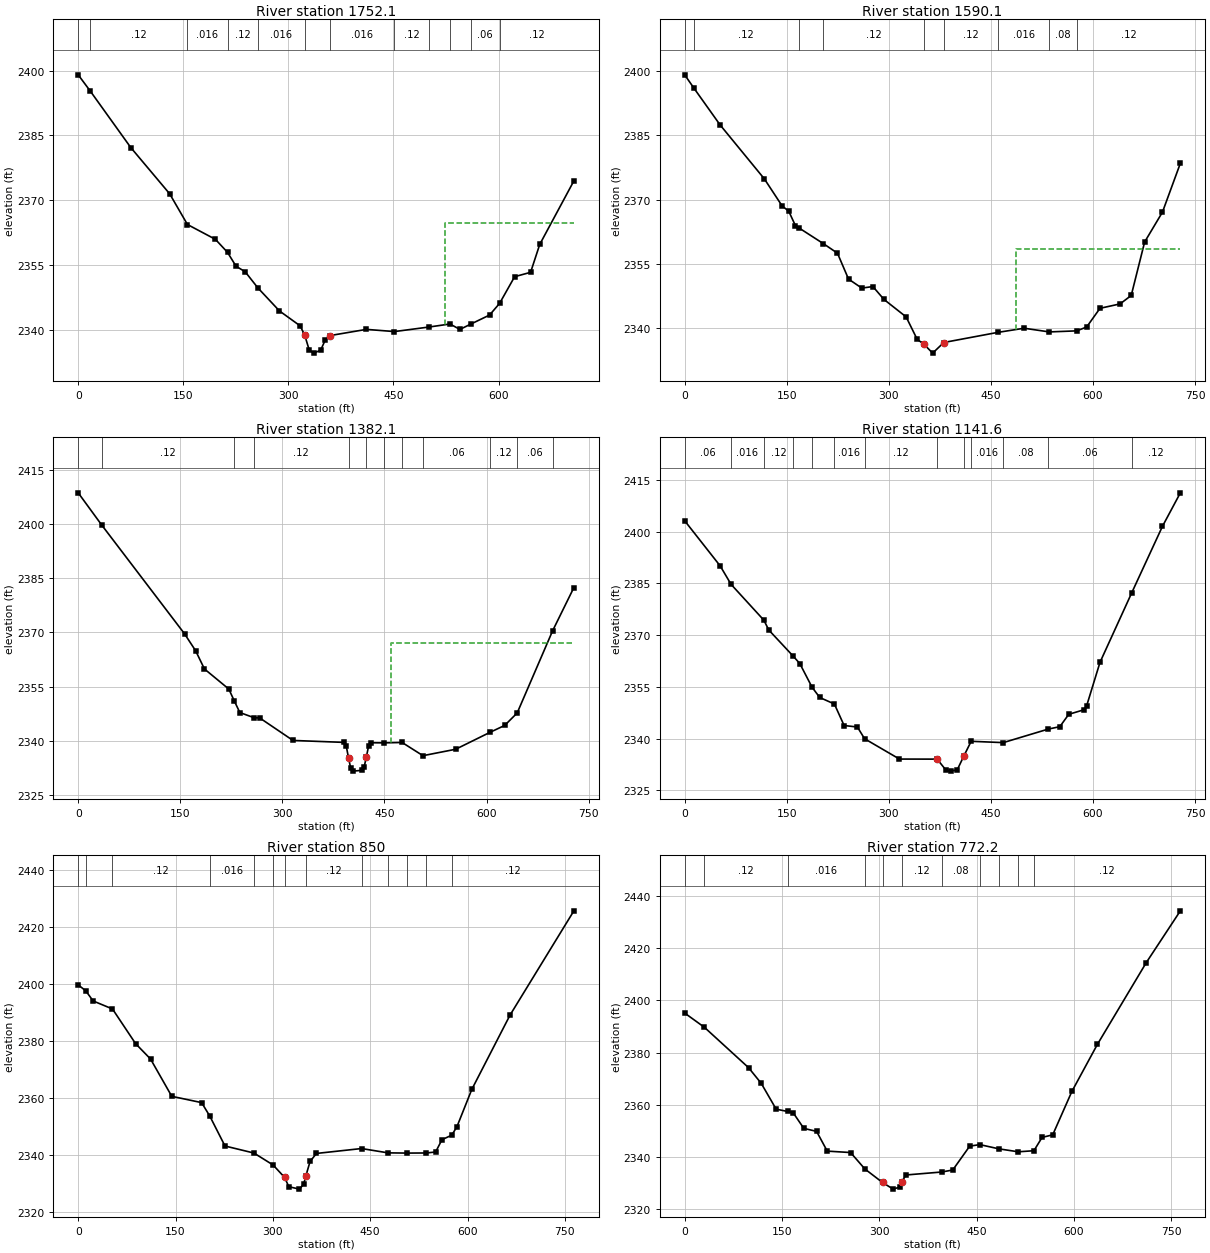
Type RM Length L Ch R = 1 ,1752.1  ,151.1,161.9,172.7
XS GIS Cut Line= 3
     2140474.241      204931.665     2140500.283       205384.79
     2140489.866      205638.263
#Sta/Elev= 30
       0 2399.01   17.242395.253    75.1 2382.19   130.6  2371.5  155.94 2364.41
   195.9 2360.98  213.132357.979   225.3 2354.77   238.4 2353.48  256.512349.754
   287.3 2344.43   316.7    2341   323.3 2338.86   329.8 2335.39   336.3 2334.68
   346.1 2335.36   352.6 2337.69   359.2 2338.73   411.4 2340.17  451.422339.662
  501.272340.725  530.712341.414   544.9 2340.16  560.272341.382   587.2 2343.48
  601.522346.176     623 2352.35   645.8 2353.36   658.8  2359.8   707.6  2374.5
#Mann= 12 ,-1 , 0
       0     .06       0   17.24     .12       0  155.94    .016       0
  213.13     .12       0  256.51    .016       0   323.3    .045       0
   359.2    .016       0  451.42     .12       0  501.27    .016       0
  530.71     .08       0  560.27     .06       0  601.52     .12       0
#XS Ineff= 2 , 0
                          523.58         2364.82
Permanent Ineff=
       F       F
Bank Sta=323.3,359.2
XS Rating Curve= 0 ,0
Exp/Cntr=0.3,0.1

Type RM Length L Ch R = 1 ,1590.1  ,198.4,208,208
XS GIS Cut Line= 3
     2140434.562      204929.718     2140343.407      205282.578
     2140248.367      205633.873
#Sta/Elev= 30
       0 2399.15   13.382396.092    52.1 2387.45   117.1 2374.86   143.2 2368.55
   152.9 2367.33   162.7 2363.96  167.282363.484  203.652359.765   224.5 2357.52
   240.8 2351.47   260.3 2349.37   276.6 2349.73   292.9 2346.72   325.4 2342.65
   341.7  2337.4   351.4  2336.3   364.4 2334.19   380.8 2336.67  459.952339.027
   498.9    2340  535.85 2339.14  576.27 2339.39   590.7 2340.29   610.3 2344.65
   639.8 2345.68   656.2 2347.65   675.9 2360.13   702.1 2367.11   728.4 2378.51
#Mann= 9 ,-1 , 0
       0     .06       0   13.38     .12       0  167.28    .016       0
  203.65     .12       0   351.4    .045       0   380.8     .12       0
  459.95    .016       0  535.85     .08       0  576.27     .12       0
#XS Ineff= 2 , 0
                          486.25         2358.57
Permanent Ineff=
       F       F
Bank Sta=351.4,380.8
XS Rating Curve= 0 ,0
Exp/Cntr=0.3,0.1

Type RM Length L Ch R = 1 ,1382.1  ,249.4,240.5,239.6
XS GIS Cut Line= 3
      2140252.27      204882.843     2140161.115      205235.703
     2140066.075      205586.998
#Sta/Elev= 30
       0 2408.56    34.52399.675   156.2 2369.62   172.5 2364.94   185.5 2359.89
   221.3 2354.34  229.362351.063   237.5 2347.85  258.342346.426   266.8 2346.35
   315.6 2340.14   390.7  2339.6     394 2338.47   397.2 2335.33   400.5 2332.43
   403.8 2331.66   416.9 2331.88   420.2 2332.82   423.5 2335.64   426.7 2338.58
     430  2339.5  449.19 2339.47  475.992339.573  506.592335.929   554.6  2337.7
  604.692342.339   626.7 2344.29  645.052347.729  697.072370.416   728.4 2382.39
#Mann= 12 ,-1 , 0
       0     .06       0    34.5     .12       0  229.36    .016       0
  258.34     .12       0   397.2    .045       0   423.5     .12       0
  449.19    .016       0  475.99     .08       0  506.59     .06       0
  604.69     .12       0  645.05     .06       0  697.07     .12       0
#XS Ineff= 2 , 0
                          460.03         2366.94
Permanent Ineff=
       F       F
Bank Sta=397.2,423.5
XS Rating Curve= 0 ,0
Exp/Cntr=0.3,0.1

Type RM Length L Ch R = 1 ,1141.6  ,302.1,291.7,280.3
XS GIS Cut Line= 3
     2140017.895      204834.232      2139926.74      205187.092
       2139831.7      205538.387
#Sta/Elev= 30
       0 2403.18    52.1  2390.1   68.24 2384.72  116.412374.327   123.6 2371.49
  159.762363.844   169.2 2361.75  187.222354.879   198.5 2351.91     220 2350.02
   234.3 2343.78   253.8 2343.35  264.35 2339.95   315.6 2334.05     371 2334.03
   384.1 2330.81   390.7 2330.55   400.5 2330.92   410.3 2334.96  420.992339.203
  468.162338.819  534.132342.736   551.3 2343.45   564.4 2347.03   587.4 2348.39
   590.7 2349.51   610.3 2362.11  657.092382.342   702.1 2401.57   728.4 2411.28
#Mann= 13 ,-1 , 0
       0     .06       0   68.24    .016       0  116.41     .12       0
  159.76     .06       0  187.22     .12       0     220    .016       0
  264.35     .12       0     371    .045       0   410.3     .12       0
  420.99    .016       0  468.16     .08       0  534.13     .06       0
  657.09     .12       0
Bank Sta=371,410.3
XS Rating Curve= 0 ,0
Exp/Cntr=0.3,0.1

Type RM Length L Ch R = 1 ,850     ,77.5,77.8,78
XS GIS Cut Line= 2
     2139663.477      204747.638     2139661.741      205511.526
#Sta/Elev= 30
       0 2399.57   11.732397.454      23 2393.92   52.85  2391.1    88.5 2378.92
   111.5 2373.53   144.2 2360.44   190.2 2358.23  202.832353.482   226.2    2343
  270.792340.532  300.322336.339     318 2331.99   324.6 2328.71     341 2327.86
   347.5 2329.62   350.8 2332.49   357.4 2337.61   367.2 2340.39  436.632342.108
  477.55 2340.59  507.092340.513  536.632340.553   550.8  2340.9   560.6 2345.22
  575.672346.806   583.6 2349.74   606.5 2362.84   665.5 2388.96   763.9 2425.56
#Mann= 13 ,-1 , 0
       0     .12       0   11.73    .016       0   52.85     .12       0
  202.83    .016       0  270.79     .08       0  300.32     .12       0
     318    .045       0   350.8     .12       0  436.63    .016       0
  477.55     .08       0  507.09     .12       0  536.63     .06       0
  575.67     .12       0
Bank Sta=318,350.8
XS Rating Curve= 0 ,0
Exp/Cntr=0.3,0.1

Type RM Length L Ch R = 1 ,772.2   ,239.1,235.9,232.9
XS GIS Cut Line= 2
     2139588.824      204740.693     2139587.088      205504.582
#Sta/Elev= 30
       0 2395.16   30.462389.677    98.4 2374.21     118 2368.18     141 2358.26
     1592357.375   167.2 2356.89   183.6  2350.9   203.3 2349.74   219.7 2342.17
   255.7 2341.62  277.72 2335.31   304.9 2330.13   321.3 2327.58   331.1 2328.35
   334.4 2330.25     341 2333.01  395.882334.145   413.1 2334.91   439.3 2344.09
  454.952344.658  484.492343.027  514.032341.908   538.22342.318   550.8 2347.43
   567.2 2348.42   596.7 2365.06     636 2383.12   711.4 2414.53   763.9 2434.39
#Mann= 11 ,-1 , 0
       0    .016       0   30.46     .12       0     159    .016       0
  277.72     .08       0   304.9    .045       0   334.4     .12       0
  395.88     .08       0  454.95    .016       0  484.49     .08       0
  514.03     .06       0   538.2     .12       0
Bank Sta=304.9,334.4
XS Rating Curve= 0 ,0
Exp/Cntr=0.3,0.1

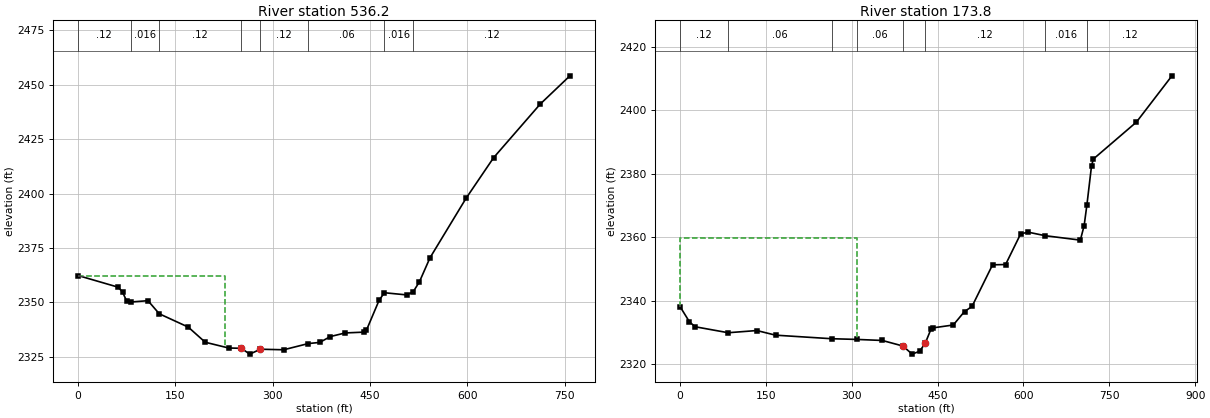
Type RM Length L Ch R = 1 ,536.2   ,347.3,362.5,352.9
XS GIS Cut Line= 2
      2139331.88      204773.679     2139396.116      205528.888
#Sta/Elev= 30
       0 2362.33    62.1 2356.95    68.6 2354.71    75.1 2350.53   80.982350.156
   107.8 2350.77  125.192344.755   169.9 2338.63     196 2331.68     232 2329.04
   251.6 2328.89   264.6 2326.22     281 2328.47   316.9 2328.22  354.842331.075
   372.4  2331.6   388.8 2334.29   411.6 2335.95     441 2336.33   444.3 2337.13
   463.9 2350.94  472.042354.423   506.4 2353.42   516.42354.856     526 2359.42
   542.3 2370.46   597.8 2397.76   640.3 2416.44   712.2 2441.09   757.9 2454.06
#Mann= 8 ,-1 , 0
       0     .12       0   80.98    .016       0  125.19     .12       0
   251.6    .045       0     281     .12       0  354.84     .06       0
  472.04    .016       0   516.4     .12       0
#XS Ineff= 2 , 0
          225.98 2361.96
Permanent Ineff=
       F       F
Bank Sta=251.6,281
XS Rating Curve= 0 ,0
Exp/Cntr=0.3,0.1

Type RM Length L Ch R = 1 ,173.8   ,203.1,173.8,144.2
XS GIS Cut Line= 3
     2139173.894      204770.207      2139081.88      205074.026
     2139219.033      205598.332
#Sta/Elev= 30
       0 2338.12    16.4 2333.34    26.2 2331.77   84.152329.879   134.2 2330.57
   166.9 2329.11  264.692327.991  308.682327.769   353.4 2327.44   389.3 2325.69
   405.6 2323.13   418.6 2324.05   428.4 2326.56   438.2  2330.9   441.5  2331.4
   477.4 2332.32     497 2336.57   510.1 2338.16     546  2351.3   568.8 2351.39
     595 2361.03     608 2361.61  637.75 2360.49   699.4 2359.09     706 2363.63
  710.942370.318     719 2382.62   722.3 2384.69   797.4 2396.32   859.4 2410.91
#Mann= 8 ,-1 , 0
       0     .12       0   84.15     .06       0  264.69     .12       0
  308.68     .06       0   389.3    .045       0   428.4     .12       0
  637.75    .016       0  710.94     .12       0
#XS Ineff= 2 , 0
          308.95 2359.67
Permanent Ineff=
       F       F
Bank Sta=389.3,428.4
XS Rating Curve= 0 ,0
Exp/Cntr=0.3,0.1

Chan Stop Cuts=-1
Use User Specified Reach Order=0
Composite Channel Slope=5